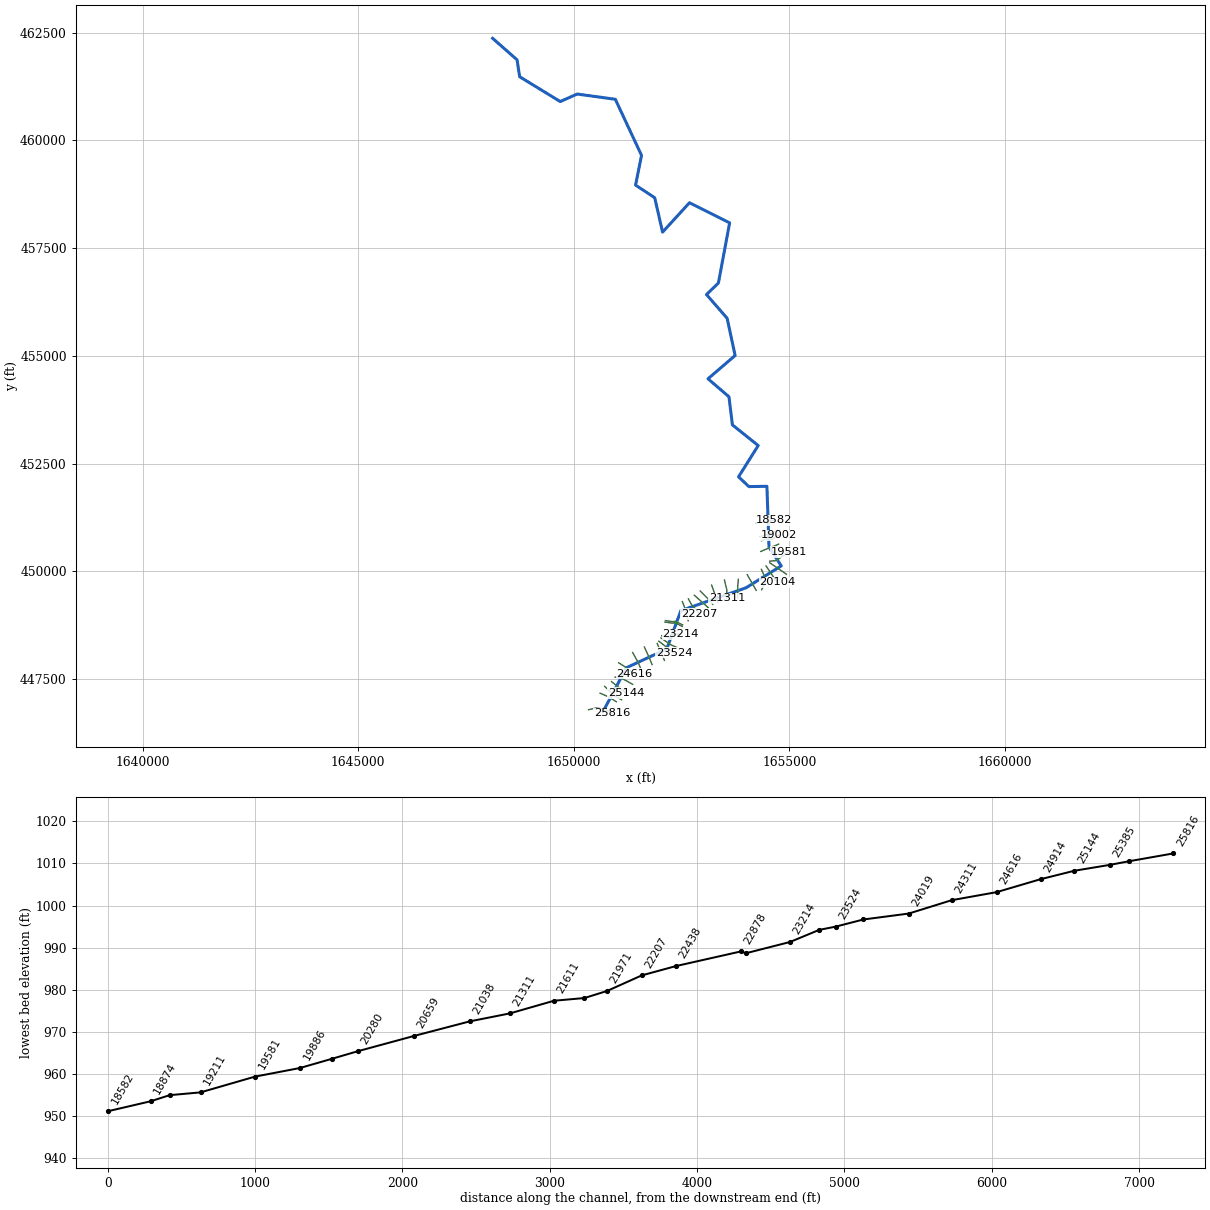
--- LaurelRnI.prj (project) ---

Proj Title=LaurelRnI
Current Plan=p01
Default Exp/Contr=0,0
English Units
Geom File=g01
Flow File=f01
Plan File=p01
BEGIN DESCRIPTION:
---------- MODELED AS PART OF WVEM CTP PROGRAM, 2025----------
Stream Name: Laurel Run I
Flood Zone: AFH
Marshall County, WV
HEC-RAS Version: RAS 6.6
Vertical Datum: NAVD88
Projection: NAD 1983 StatePlane West Virginia N FIPS 4701 (US Feet)
Terrain: 1-meter West Virginia FEMA R3 South Central (collected 2018-2019)
Land Use: 2024 NLCD
Hydrologic Method:
Duda et al., "Estimation of magnitude and frequency of floods for rural, unregulated streams in and near Virginia and West Virginia." September 8, 2025.
Additional Model Notes:
None
END DESCRIPTION:
DSS Export Rating Curves= 0
DSS Export Rating Curve Sorted= 0
DSS Export Volume Flow Curves= 0
DXF OffsetX= 0
DXF OffsetY= 0
DXF ScaleX= 0
DXF ScaleY= 0

--- LaurelRnI.p01 (plan) ---

Plan Title=Floodplain
Program Version=6.60
Geom File=g01
Flow File=f01
Subcritical Flow
K Sum by GR= 0
Std Step Tol= 0.01
Critical Tol= 0.01
Num of Std Step Trials= 20
Max Error Tol= 0.3
Flow Tol Ratio= 0.001
Split Flow NTrial= 30
Split Flow Tol= 0.02
Split Flow Ratio= 0.02
Log Output Level= 0
Friction Slope Method= 1
Unsteady Friction Slope Method= 2
Unsteady Bridges Friction Slope Method= 1
Parabolic Critical Depth
Global Vel Dist= 0 , 0 , 0
Global Log Level= 0
CheckData=False
Encroach Param=-1 ,0,0, 0
Flow Ratio Tolerance=0.1
Flow Ratio Min Ratio=0.5
Flow Ratio Max Ratio=4
Flow Ratio Max Iterations= 10
Mapping Interval=1HOUR
Computation Time Step Use Courant=        0
Computation Time Step Use Time Series=    0
Computation Time Step Count To Double=0
Computation Time Step Max Doubling=0
Computation Time Step Max Halving=0
Computation Time Step Residence Courant=0
Run HTab= 0
Run UNet= 0
Run Sediment= 0
Run PostProcess= 0
Run WQNet= 0
Run RASMapper=-1
UNET Theta= 0
UNET Theta Warmup= 0
UNET ZTol= 0
UNET ZSATol= 0
UNET MxIter= 0
UNET Max Iter WO Improvement= 0
UNET MaxInSteps= 0
UNET DtIC= 0
UNET DtMin= 0
UNET MaxCRTS= 0
UNET WFStab= 0
UNET SFStab= 0
UNET WFX= 1
UNET SFX= 1
UNET Gravity=32.17405
UNET 1D Methodology=Finite Difference
UNET DSS MLevel= 1
UNET Pardiso=0
UNET DZMax Abort= 0
UNET Use Existing IB Tables= 0
UNET Froude Reduction=False
UNET Froude Limit= 0
UNET Froude Power= 0
UNET D1 Cores= 0
UNET WindReference=Eulerian
UNET WindDragFormulation=Hsu (1988)
UNET D2 Coriolis=0
UNET D2 Cores= 0
UNET D2 Theta= 1
UNET D2 Theta Warmup= 1
UNET D2 Z Tol= 0.01
UNET D2 Volume Tol= 0.01
UNET D2 Max Iterations= 20
UNET D2 Advanced Convergence=0
UNET D2 WS Max Tol=0.15
UNET D2 WS RMS Tol=0.002
UNET D2 WS Stall Tol=1
UNET D2 Equation= 0
UNET D2 RampUpFraction=0.1
UNET D2 TimeSlices= 1
UNET D2 Turbulence Formulation=Non-Conservative (original)
UNET D2 Eddy Viscosity=0.3
UNET D2 Transverse Eddy Viscosity=0.1
UNET D2 Smagorinsky Mixing=0
UNET D2 BCVolumeCheck=0
UNET D2 Cores=0
UNET D2 SolverType=PARDISO (Direct)
UNET D2 Minimum Iterations= 3
UNET D2 Maximum Iterations= 30
UNET D2 Restart Number= 10
UNET D2 Relaxation Coeff=1.3
UNET D2 SOR Precondition Iterations= 10
UNET D2 ILUT Maximum Fill= 8
UNET D2 ILUT Tolerance=1E-08
UNET D2 Convergence Tolerance=0.00001
PS Theta= 1
PS WS Tol= 0.01
PS Volume Tol= 0.01
PS Max Iterations= 20
PS Equation= 0
PS Advance Time Step=-1
PS Target Courant=0.9
PS Time Slices= 1
PS Iterate With 2D=0
PS Project Initial WSE from DS=-1
PS Ramp Up Initial WSE from US=-1
PS Cores=0
UNET D1D2 MaxIter= 0
UNET D1D2 ZTol=0.01
UNET D1D2 QTol=0.1
UNET D1D2 MinQTol=1
Write IC File= 0
Write IC File at Fixed DateTime=0
Write IC File at Sim End=0
Echo Input=False
Echo Parameters=False
Echo Output=False
Write Detailed= 0
HDF Write Warmup=0
HDF Write Time Slices=0
HDF Flush=0
HDF Compression= 1
HDF Chunk Size= 1
HDF Spatial Parts= 1
HDF Use Max Rows=0
HDF Fixed Rows= 1
Calibration Method= 0
Calibration Iterations= 20
Calibration Max Change=0.05
Calibration Tolerance=0.2
Calibration Maximum=1.5
Calibration Minimum=0.5
Calibration Optimization Method= 1
WQ AD Non Conservative
WQ ULTIMATE=-1
WQ Max Comp Step=1HOUR
WQ Output Interval=15MIN
WQ Output Selected Increments= 0
WQ Create Restart=0
WQ Fixed Restart=0
WQ System Summary=0
WQ Write To DSS=0
Sorting and Armoring Iterations= 10
XS Update Threshold= 0.02
Bed Roughness Predictor= 0
Processes Affected by Predictor=Sediment Only
Hydraulics Update Threshold= 0.02
Energy Slope Method= 1
Volume Change Method= 1
Sediment Retention Method= 0
Sediment TS Multiplier= 1
Warm Up Method= 0
XS Weighting Method= 0
Number of US Weighted Cross Sections= 1
Number of DS Weighted Cross Sections= 1
Upstream XS Weight=0
Main XS Weight=1
Downstream XS Weight=0
Number of DS XS's Weighted with US Boundary= 1
Upstream Boundary Weight= 1
Weight of XSs Associated with US Boundary= 0
Number of US XS's Weighted with DS Boundary= 1
Downstream Boundary Weight= 0.5
Weight of XSs Associated with DS Boundary= 0.5
Percentile Method= 0
Sediment Output Level= 3
Mass or Volume Output= 0
Output Increment Type= 1
Profile and TS Output Increment= 1
Transport Output Increment 1
XS Output Flag= 0
XS Output Increment= 10
Read HDF5 Sediment Hotstart= 0
Sediment Hotstart Type= 0
Write Gradation File= 0
Read Gradation Hotstart= 0
Write HDF5 File= 1
Write Binary Output= 1
Write DSS Sediment File= 0
DSS Sediment Output Type= 1
SV Curve= 0
Specific Gage Flag= 0
Subcell Erosion Methods= 0
Subcell Deposition Methods= 0
Advection Scheme= 1
Matrix Solver= 0
Implicit Weighting Factor= 1
Maximum Outer Loop Convergence Iterations= 5
Convergence Maximum Absolute= 0.001
Convergence RMSE= 0.0001
Grain Fractions Max Abs Error= 0.001
Max Subgrid Regions= 1
Max Subgrid Length Scale= 3.402823E+38
Initial Layer Thickness= 3
Min Layer Thickness= 0.1
Max Layer Thickness= 6
Number of Layers= 5

--- LaurelRnI.f01 (steady flow) ---

Flow Title=Flow
Program Version=6.60
Number of Profiles= 1
Profile Names=P100yr
River Rch & RM=LaurelRnI,Main,25816
    1620
River Rch & RM=LaurelRnI,Main,20659
    1980
River Rch & RM=LaurelRnI,Main,19002
    2210
River Rch & RM=LaurelRnI,Main,10209
    2460
Boundary for River Rch & Prof#=LaurelRnI,Main            , 1
Up Type= 0
Dn Type= 3
Dn Slope=0.011105
DSS Import GetInterval= 0
DSS Import GetPeak= 0
DSS Import FillOption= 0

--- LaurelRnI.g01 (geometry) ---

Geom Title=Geometry
Program Version=6.60

River Reach=LaurelRnI       ,Main
Reach XY= 30
1650675.44455057446745.968080285     1651219.638      447766.111
     1652153.344      448199.066        1652482.        449089.5
       1653993.5        449620.5     1654809.567      450128.433
     1654526.063      450562.751     1654476.871      451975.092
     1654059.382      451967.972     1653818.598      452194.517
      1654275.57      452920.752     1653676.846      453400.379
     1653596.666      454052.219     1653110.874      454469.926
     1653739.631      455010.137     1653554.512      455873.594
     1653075.533      456425.067     1653352.383      456691.561
     1653612.119      458087.902      1652681.41      458554.835
     1652057.379      457873.008     1651875.334      458671.091
     1651430.822      458964.304     1651569.985      459653.646
     1650961.795      460955.466     1650078.879      461077.072
     1649684.156       460903.19     1648743.804      461478.449
     1648682.956      461871.564     1648117.207      462369.622

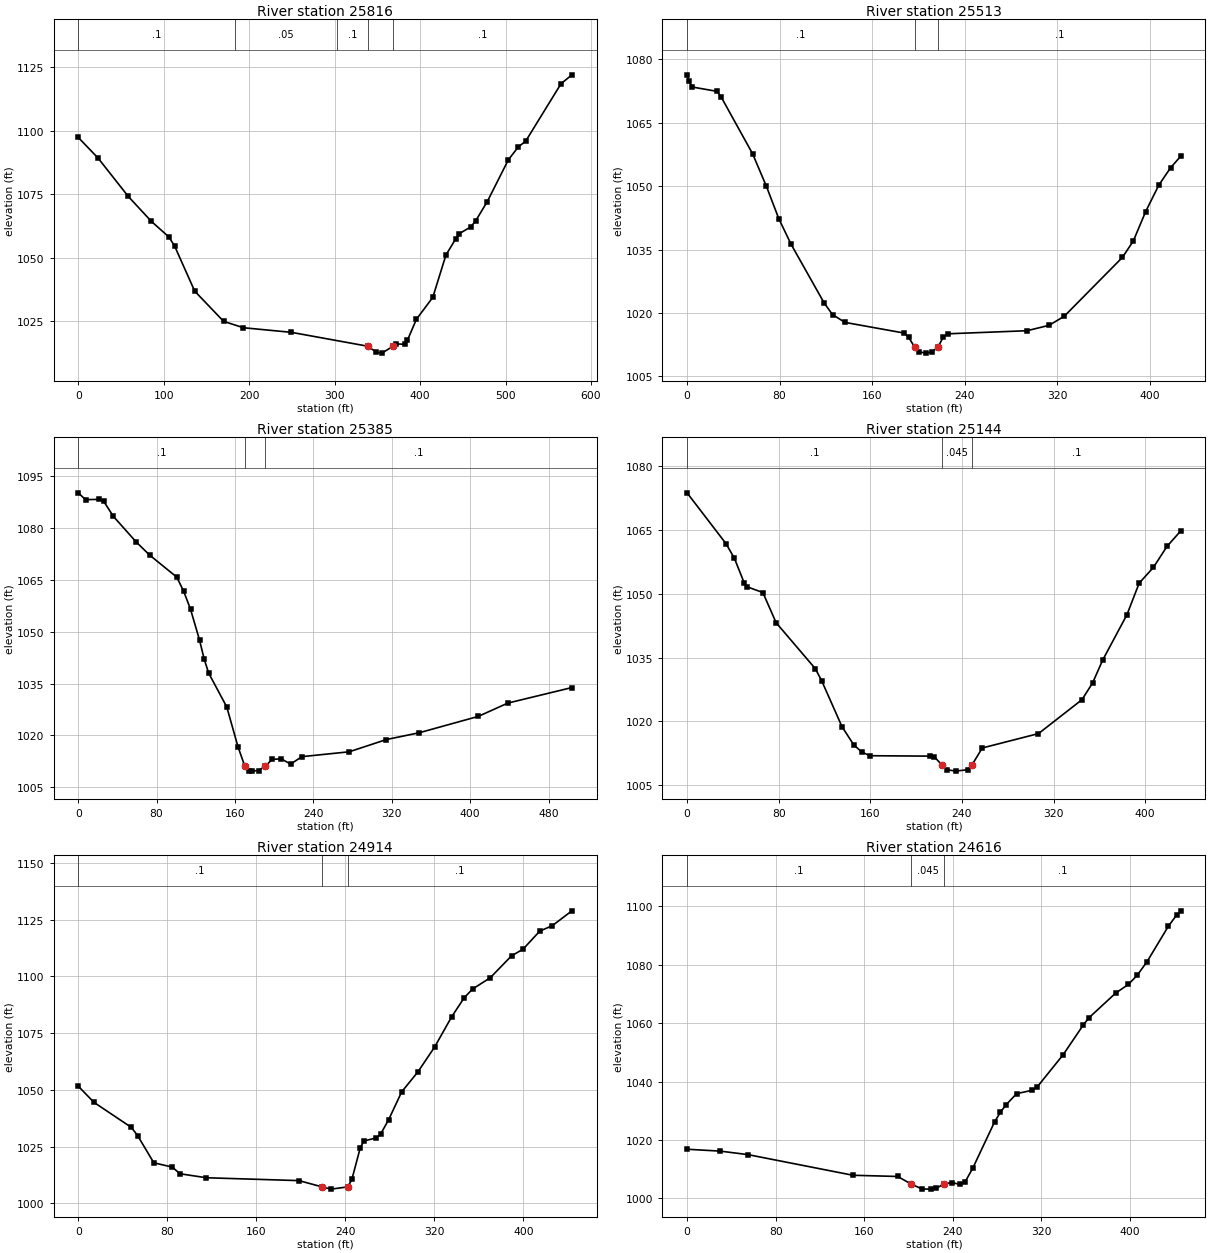
Type RM Length L Ch R = 1 ,25816   ,309.1,303.1,299.1
XS GIS Cut Line= 4
1650339.25335276446790.0716682961650507.36489402446831.165600605
1650724.04199165446803.1470103941650882.81400284446706.015897664
#Sta/Elev= 30
       0 1097.44    23.3 1089.25    58.6 1074.14    85.7  1064.3     106 1058.21
   112.7 1054.67   136.3 1036.83   170.1 1024.92   193.3  1022.4   249.5 1020.58
   338.9 1015.11   348.8 1012.75   355.4 1012.39  368.441015.121   371.9 1016.05
   381.9 1015.86   385.2 1017.46   395.7 1025.72   414.9 1034.37   430.3 1051.08
   441.8 1057.48   445.7 1059.44   459.3 1062.16   464.9 1064.45   478.5 1072.03
   503.4 1088.65   514.9 1093.64   523.7    1096   564.9 1118.57   577.7  1122.1
#Mann= 5 ,-1,0
       0      .1       0  183.06     .05       0  303.06      .1       0
   338.9    .045       0  368.44      .1       0
Bank Sta=338.9,368.44
XS Rating Curve= 0 ,0
Exp/Cntr(USF)=0,0
Exp/Cntr=0.3,0.1

Type RM Length L Ch R = 1 ,25513   ,128.4,128,122.7
XS GIS Cut Line= 6
1650608.56052743447173.9989944991650690.16042984447139.764811009
1650759.45097367447109.3199900091650846.96687476447060.754798427
1650910.96280976447021.6456246671650985.62440585446976.017763168
#Sta/Elev= 30
       0 1076.35     1.5 1074.91     4.5 1073.47    25.9 1072.44    29.4 1071.16
    56.7 1057.66    68.6 1049.99    79.3 1042.34    89.9 1036.29   118.6 1022.35
   125.8 1019.63   136.5 1017.79   187.8 1015.26   191.5 1014.26  196.731011.976
   200.1 1010.85   206.5 1010.52   211.9  1010.8  216.951011.975   221.5 1014.29
   225.3 1015.09   293.9 1015.82     313  1017.1   326.1 1019.24   376.4 1033.17
   385.8 1037.04   396.5 1044.01   407.8 1050.24     418 1054.36   426.8  1057.1
#Mann= 3 ,-1,0
       0      .1       0  196.73    .045       0  216.95      .1       0
Bank Sta=196.73,216.95
XS Rating Curve= 0 ,0
Exp/Cntr(USF)=0,0
Exp/Cntr=0.3,0.1

Type RM Length L Ch R = 1 ,25385   ,235.1,241.3,240.6
XS GIS Cut Line= 3
1650715.25591145447332.3668745691650926.62383842447121.991285286
1651106.23695946447021.765179071
#Sta/Elev= 30
       0 1090.12     7.5 1088.15    21.4 1088.23    26.1 1087.62    35.9 1083.31
      59 1075.96    72.8 1072.14   100.6 1065.75   107.6 1061.67   114.6 1056.49
   123.8 1047.56   128.5 1042.13   133.1 1038.03   151.6 1028.22   163.2 1016.59
  169.97 1011.16   174.8 1009.69   177.2 1009.67   184.1 1009.85   191.1 1011.14
     198 1013.09   207.3 1013.21   216.8  1011.7   228.2 1013.85   276.6 1015.26
   314.5  1018.8   348.3 1020.78   408.4  1025.5   438.5 1029.34   503.9 1033.83
#Mann= 3 ,-1,0
       0      .1       0  169.97    .045       0   191.1      .1       0
Bank Sta=169.97,191.1
XS Rating Curve= 0 ,0
Exp/Cntr(USF)=0,0
Exp/Cntr=0.3,0.1

Type RM Length L Ch R = 1 ,25144   ,225.2,230,230.9
XS GIS Cut Line= 2
 1650872.1920384447443.1480999121651212.23104394447178.092229552
#Sta/Elev= 30
       0  1073.8      34 1061.84    41.3 1058.42      50 1052.55    52.1  1051.7
    66.2 1050.33    77.8 1043.21     112  1032.4   117.6 1029.53   135.4 1018.69
   145.6 1014.45   152.6 1012.76   159.7  1011.9   211.8  1011.8     216  1011.6
  222.53 1009.76   227.4 1008.59   234.5 1008.27   245.1  1008.6   248.9 1009.76
   257.8 1013.72   306.9 1017.11   344.9  1025.1   354.2 1029.07     363 1034.45
   384.1 1045.08   394.8 1052.53   407.3 1056.26   419.1 1061.18   431.1 1064.83
#Mann= 3 ,-1,0
       0      .1       0  222.53    .045       0   248.9      .1       0
Bank Sta=222.53,248.9
XS Rating Curve= 0 ,0
Exp/Cntr(USF)=0,0
Exp/Cntr=0.3,0.1

Type RM Length L Ch R = 1 ,24914   ,298,297.6,288.5
XS GIS Cut Line= 6
 1650956.5404745447548.6150431781651049.03668059447528.088509426
1651129.43973501447505.8976089211651221.56980009447460.204130754
1651286.82163809447423.2284829171651362.94878243447380.090445846
#Sta/Elev= 30
       0 1051.63    14.1  1044.5    47.8 1033.43    53.4 1029.79    67.9 1017.86
    84.5 1015.96    91.4 1013.03   115.2 1011.27   198.3 1010.01  218.941007.264
   227.1 1006.26  242.311007.259   245.9 1010.67   253.3 1024.36   256.5 1027.45
   267.9 1028.85   271.6 1030.45   278.9 1036.89   290.6 1049.14   305.1 1057.88
   320.3 1068.98   335.4 1082.12   346.7 1090.55   354.3 1094.44   370.1 1099.36
   389.3 1109.05   399.5 1111.92   414.6 1119.91   425.9 1122.33   443.5 1128.86
#Mann= 3 ,-1,0
       0      .1       0  218.94    .045       0  242.31      .1       0
Bank Sta=218.94,242.31
XS Rating Curve= 0 ,0
Exp/Cntr(USF)=0,0
Exp/Cntr=0.3,0.1

Type RM Length L Ch R = 1 ,24616   ,308.1,305,296.5
XS GIS Cut Line= 6
1651039.95041268 447879.323699341651114.22487043447833.136127666
1651177.89928375447793.540406346 1651258.5716946447727.673412085
1651323.03088325447676.4018610861651403.18754709447622.299607083
#Sta/Elev= 30
       0 1016.84    30.1 1016.19    55.1 1014.99   149.8 1007.93   190.2 1007.52
   201.9 1005.01   212.2 1003.23   220.5 1003.19   224.9 1003.45   232.2 1005.02
   239.2 1005.44   246.2 1004.81   250.9 1005.59   257.9 1010.31   277.7 1026.24
   282.9 1029.48   288.1 1032.07   297.5 1035.85   311.5 1037.01   316.2 1038.19
   339.6  1049.2   357.6 1059.28   362.8  1061.8   386.9 1070.24   398.5 1073.25
   406.4 1076.37   415.1  1080.9   434.5 1093.11     442 1096.98   445.7 1098.41
#Mann= 3 ,-1,0
       0      .1       0   201.9    .045       0   232.2      .1       0
Bank Sta=201.9,232.2
XS Rating Curve= 0 ,0
Exp/Cntr(USF)=0,0
Exp/Cntr=0.3,0.1

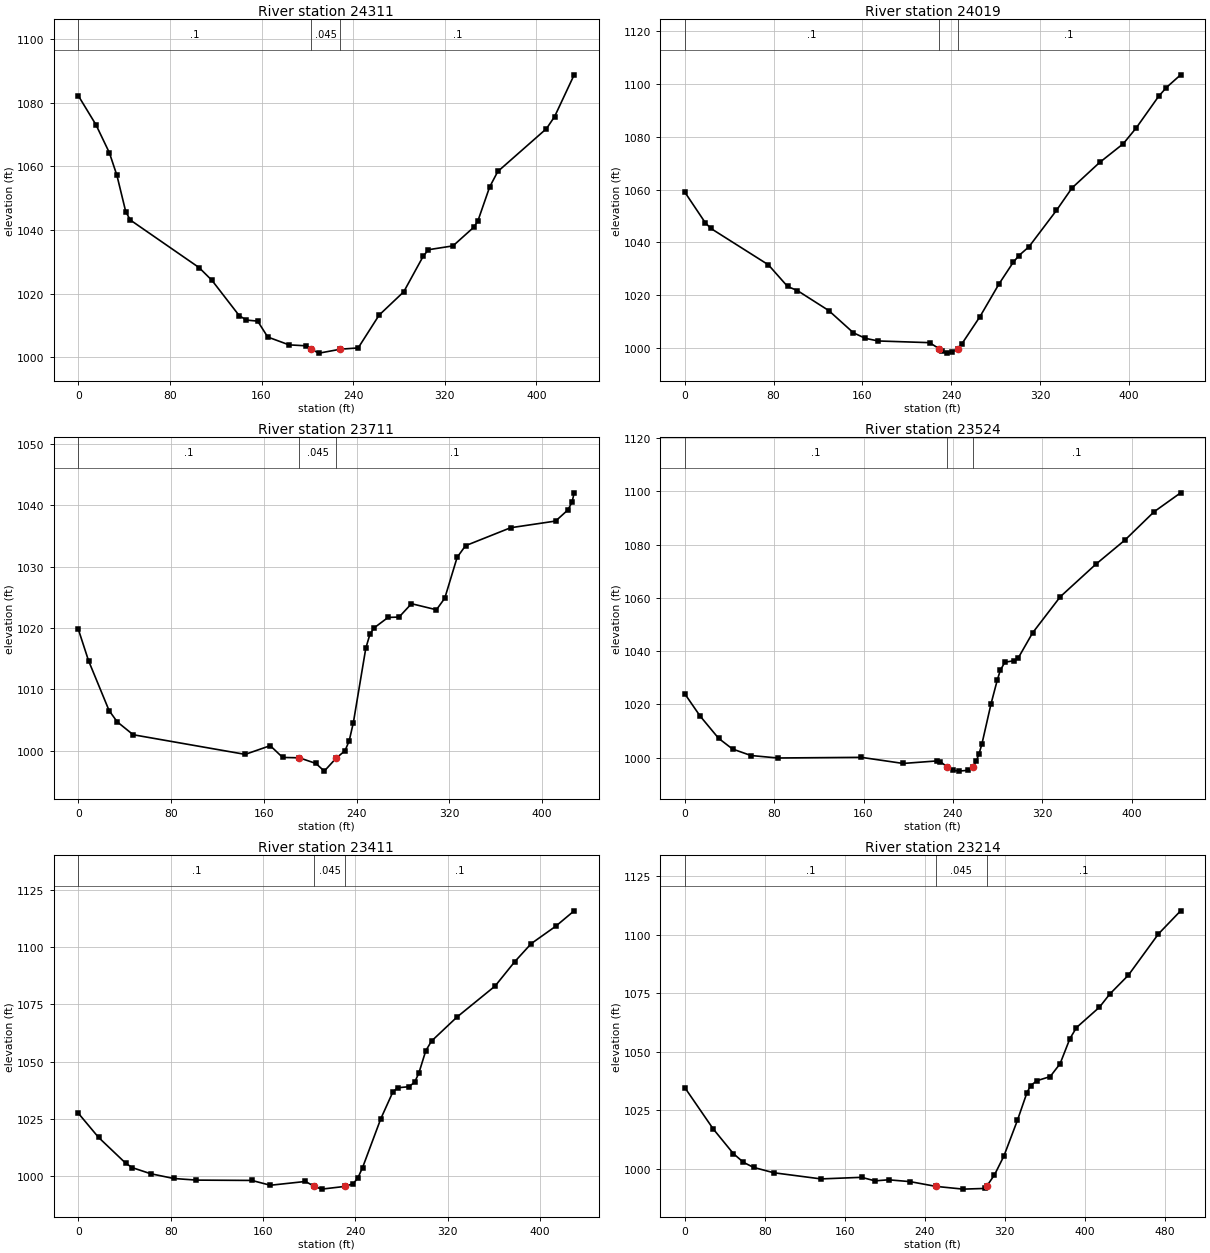
Type RM Length L Ch R = 1 ,24311   ,291.3,292,288.9
XS GIS Cut Line= 6
1651363.70731109  448118.13883851651406.06024475 448041.57698375
1651442.36069709447975.9570362571651490.68802826447887.847960502
1651522.26047167447815.8989574161651556.59111167447731.170124263
#Sta/Elev= 30
       0 1082.25    15.4 1073.12    27.1 1064.32    33.7 1057.19    41.4 1045.78
    45.4 1043.15   105.4  1028.2   116.7 1024.17   140.5 1013.08   146.7 1011.68
   156.6 1011.35   165.4 1006.35     184 1003.88   198.5 1003.59  202.931002.513
   210.3 1001.28  228.921002.515   244.4 1002.92   262.7 1013.25   284.2 1020.59
   301.1 1031.71   305.7 1033.81   327.2 1035.02   345.1 1040.81   348.8 1042.74
   359.2 1053.55   366.3 1058.42   408.8 1071.89   415.9 1075.67     433 1088.83
#Mann= 3 ,-1,0
       0      .1       0  202.93    .045       0  228.92      .1       0
Bank Sta=202.93,228.92
XS Rating Curve= 0 ,0
Exp/Cntr(USF)=0,0
Exp/Cntr=0.3,0.1

Type RM Length L Ch R = 1 ,24019   ,306.4,308.1,308.3
XS GIS Cut Line= 3
1651635.26353514448246.0033991961651750.10485314 447995.30970376
1651814.31069962447836.882304052
#Sta/Elev= 30
       0 1059.02    18.4 1047.47    23.3 1045.33    75.3 1031.52    92.6 1023.32
   101.4 1021.78   129.7  1014.2   151.9 1005.79   162.7 1003.69   174.3  1002.7
   220.5 1002.06  228.94  999.84   231.3  998.83   236.2   998.1   241.1  998.59
   245.7  999.84   249.3 1001.41   265.9 1011.89   283.3 1024.43   295.8  1032.4
     301 1035.02     310 1038.31   334.8 1052.09   348.9 1060.62   373.7 1070.23
     395 1077.32   406.8 1083.36   426.9 1095.27   433.9  1098.6   446.7  1103.4
#Mann= 3 ,-1,0
       0      .1       0  228.94    .045       0   245.7      .1       0
Bank Sta=228.94,245.7
XS Rating Curve= 0 ,0
Exp/Cntr(USF)=0,0
Exp/Cntr=0.3,0.1

Type RM Length L Ch R = 1 ,23711   ,176.5,187,189.1
XS GIS Cut Line= 6
 1651933.5700165448329.2850697491651967.28451601448245.873163089
1651997.57251318448177.261095583 1652037.9556345448085.777682751
1652067.91587642 448017.020602421652100.31541793447935.573586836
#Sta/Elev= 30
       0 1019.81     8.8 1014.69    26.5 1006.57    33.5 1004.73    47.3 1002.62
   143.9  999.42   165.5 1000.84   176.2  998.92   190.6  998.86   204.9  997.94
   212.1  996.69   222.3  998.79     230 1000.02   233.6 1001.64   237.2 1004.61
   247.9 1016.71   251.5 1019.02   255.1 1020.04   267.1 1021.74   276.6  1021.8
   287.3 1023.98   308.8 1022.99     316 1024.87   326.7 1031.54   333.9 1033.43
   372.8 1036.36   411.6 1037.45   422.2 1039.26   425.8 1040.54   427.6 1042.05
#Mann= 3 ,-1,0
       0      .1       0   190.6    .045       0   222.3      .1       0
Bank Sta=190.6,222.3
XS Rating Curve= 0 ,0
Exp/Cntr(USF)=0,0
Exp/Cntr=0.3,0.1

Type RM Length L Ch R = 1 ,23524   ,107.9,113,107.7
XS GIS Cut Line= 2
1651969.92602706448380.7900157091652322.20590534448110.874165308
#Sta/Elev= 30
       0    1024    13.7 1015.66    30.3 1007.29    42.7  1003.3    59.2 1000.86
    83.1  999.93     158 1000.17   195.4  997.88   225.8  998.83   228.7  998.53
  235.09  996.54   239.9  995.34   245.2     995   253.5  995.31   257.6  996.54
   260.9  998.78   263.3 1001.44   265.9 1005.12   274.1 1020.25   279.6 1029.02
   282.4 1032.83   286.5 1035.87   294.8 1036.42   298.4 1037.41   311.3 1046.87
   336.1 1060.43   367.7 1072.54     394  1081.7     420 1092.29   443.8 1099.41
#Mann= 3 ,-1,0
       0      .1       0  235.09    .045       0   257.6      .1       0
Bank Sta=235.09,257.6
XS Rating Curve= 0 ,0
Exp/Cntr(USF)=0,0
Exp/Cntr=0.3,0.1

Type RM Length L Ch R = 1 ,23411   ,180.8,197.6,237.5
XS GIS Cut Line= 6
1652021.09116693448454.6890184281652093.08642976448404.960443333
1652154.79660818448362.3355285821652237.07629925448305.502636999
1652305.85962626448271.4525082561652389.08321309448235.998839006
#Sta/Elev= 30
       0 1027.39    17.5 1016.84    41.1 1005.52    46.8  1003.6    62.7 1000.95
    82.7  998.87   102.4  998.16   150.4  998.02   166.4  995.91   196.8  997.57
  204.63995.4033   210.9  994.22  231.01995.4037   238.2   996.6   242.2  999.05
   246.3  1003.6   262.1 1024.96   272.6  1036.7   276.8 1038.53   286.4 1038.98
   291.4 1040.91   295.1 1044.92   301.1 1054.71   306.1 1058.94     328 1069.37
   361.2    1083   378.2 1093.63   392.5 1101.54   413.7 1109.12   429.7 1115.87
#Mann= 3 ,-1,0
       0      .1       0  204.63    .045       0  231.01      .1       0
Bank Sta=204.63,231.01
XS Rating Curve= 0 ,0
Exp/Cntr(USF)=0,0
Exp/Cntr=0.3,0.1

Type RM Length L Ch R = 1 ,23214   ,308.2,297.9,266.9
XS GIS Cut Line= 4
1652038.64783617448506.037930243 1652237.3883688 448458.10574328
1652279.36425289448543.8437192891652475.41606834448543.667931838
#Sta/Elev= 30
       0  1034.7    28.3 1017.12    48.5 1006.55    58.7 1002.78    68.8 1000.63
      89  998.34   136.3  995.71   176.8  996.39   190.3  994.88   203.8  995.33
   225.4  994.55   251.2  992.52   278.4  991.35   299.9  991.64  301.87  992.51
   309.8  997.44   319.2 1005.47   332.7 1020.68   342.1 1032.31   345.9 1035.57
   352.4 1037.66   365.5  1039.4   375.4 1044.87   385.2 1055.56   391.8 1060.32
   414.8 1069.03   425.1 1074.62   443.7 1082.67   473.8 1100.31     496 1110.17
#Mann= 3 ,-1,0
       0      .1       0   251.2    .045       0  301.87      .1       0
Bank Sta=251.2,301.87
XS Rating Curve= 0 ,0
Exp/Cntr(USF)=0,0
Exp/Cntr=0.3,0.1

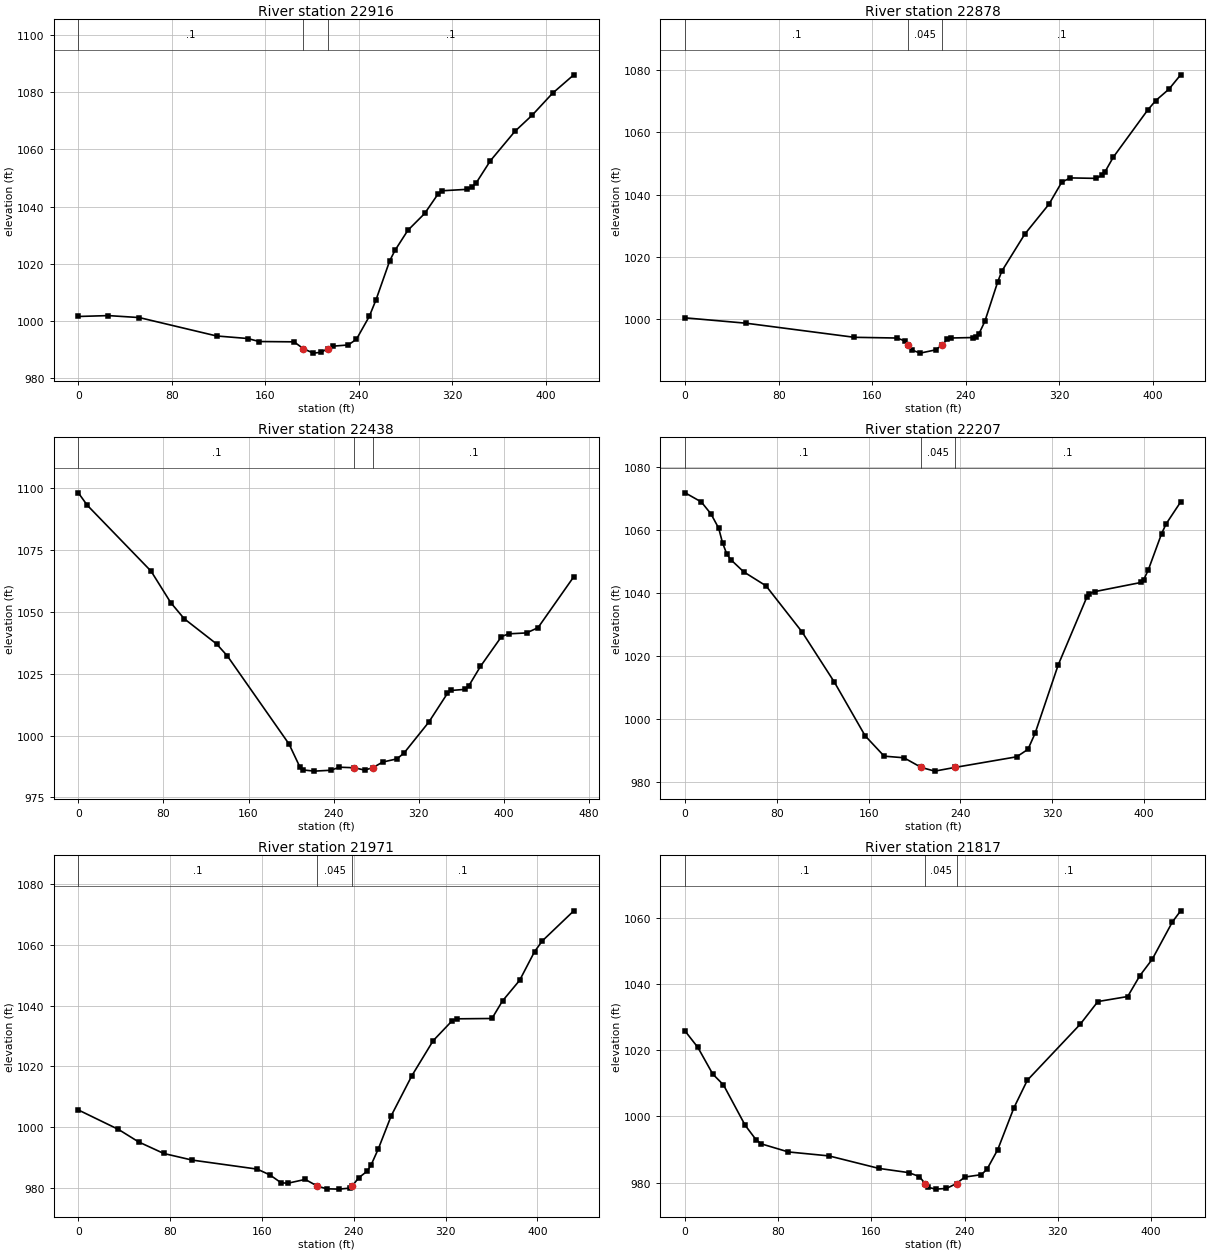
Type RM Length L Ch R = 1 ,22916   ,35.6,37.7,39.5
XS GIS Cut Line= 4
 1652112.9794577448823.5226787911652284.47537475448799.511657864
1652345.04614039448807.9785390821652514.69667045448723.130862614
#Sta/Elev= 30
       0 1001.52    25.7 1001.83    52.1 1001.14   118.3   994.7   144.9  993.81
   154.8  992.75   184.6  992.64   192.5  990.27   201.1  988.69   207.8  988.98
  213.35  990.26   217.7  991.12     231  991.55     238  993.55     249 1001.54
   254.8 1007.41   266.5 1021.04     271 1024.67     282 1031.68   296.4 1037.58
   307.6 1044.26   311.3 1045.53     333 1046.04     337 1046.81   340.7 1048.42
   352.6 1056.03   373.7 1066.37   388.4 1071.99   405.8 1079.66     424 1086.12
#Mann= 3 ,-1,0
       0      .1       0   192.5    .045       0  213.35      .1       0
Bank Sta=192.5,213.35
XS Rating Curve= 0 ,0
Exp/Cntr(USF)=0,0
Exp/Cntr=0.3,0.1

Type RM Length L Ch R = 1 ,22878   ,451.4,439.7,413.5
XS GIS Cut Line= 4
1652122.85424642448858.4503066021652294.35016347448834.439285675
1652354.92092911448842.9061668931652524.57145917448758.058490425
#Sta/Elev= 30
       0 1000.42    52.1   998.7   144.8  994.17   181.3  993.94   187.9  993.02
   190.6  991.75   194.5  990.03   201.1  989.09   214.4  990.14  220.09 991.791
   224.3  993.55   227.6  993.95   246.6   994.1     249  994.36   251.5  995.37
   256.4  999.25   267.3 1011.79   270.9 1015.38   290.6  1027.3   311.3 1036.92
   322.3 1044.02   329.6 1045.37   351.7 1045.22   356.6  1046.2   359.1 1047.22
   366.4 1052.05   395.7 1067.12   402.7 1070.21     414 1073.88     424 1078.48
#Mann= 3 ,-1,0
       0      .1       0   190.6    .045       0  220.09      .1       0
Bank Sta=190.6,220.09
XS Rating Curve= 0 ,0
Exp/Cntr(USF)=0,0
Exp/Cntr=0.3,0.1

Type RM Length L Ch R = 1 ,22438   ,226.9,231.6,236.5
XS GIS Cut Line= 3
1652515.63873425449300.1325374991652580.54448274449136.400033191
1652651.18115506448855.567391094
#Sta/Elev= 30
       0 1098.21     8.4 1093.19    68.4 1066.51    86.9 1053.77    99.5 1047.29
   129.9 1037.09     140 1032.27   198.1  996.55   208.2  987.33   211.6  986.08
   221.8  985.62   237.5  985.98   245.4  987.21   259.3  986.98   269.1  986.05
  276.78  986.98     286  989.28   299.6  990.59   306.3  993.02   329.4 1005.43
   346.9 1017.05   350.3 1018.25   363.8 1018.71   367.2 1020.25     378    1028
   397.7 1040.02   404.4 1041.16   421.3 1041.53   432.1 1043.66   465.7 1064.27
#Mann= 3 ,-1,0
       0      .1       0   259.3    .045       0  276.78      .1       0
Bank Sta=259.3,276.78
XS Rating Curve= 0 ,0
Exp/Cntr(USF)=0,0
Exp/Cntr=0.3,0.1

Type RM Length L Ch R = 1 ,22207   ,231.3,235.5,233.8
XS GIS Cut Line= 6
1652656.11975251449363.8686304991652698.12623018449283.503961846
1652737.72916934449216.8561292591652806.64996326449143.950763255
1652855.68234551449086.8344076721652903.63402125449012.530750498
#Sta/Elev= 30
       0 1071.94    14.1 1069.04    22.5 1065.24    29.2 1060.72    32.6 1056.04
    36.4 1052.38    40.1 1050.58      51 1046.82    70.5 1042.36   101.9 1027.72
   130.1 1011.75     157  994.64   173.6  988.17   190.8  987.66  206.01  984.58
   217.7  983.41  235.18984.5811   289.2  987.97     299  990.34   305.2   995.4
   325.4 1017.19   350.3  1038.7   352.6 1039.87   357.4 1040.52   397.7 1043.43
     400 1044.34   403.9 1047.33   415.6 1058.97   419.5 1062.04   432.2 1069.03
#Mann= 3 ,-1,0
       0      .1       0  206.01    .045       0  235.18      .1       0
Bank Sta=206.01,235.18
XS Rating Curve= 0 ,0
Exp/Cntr(USF)=0,0
Exp/Cntr=0.3,0.1

Type RM Length L Ch R = 1 ,21971   ,155.9,154.2,153.5
XS GIS Cut Line= 2
1652794.66579796449446.9742919481653116.40728424449159.100330536
#Sta/Elev= 30
       0 1005.71      35  999.31    52.6   995.2    74.5  991.41    99.1  989.25
   155.9  986.28     167  984.36   176.8  981.76   182.8  981.67   197.7   982.9
  208.27980.7026   216.3  979.82   227.1  979.71   236.9  980.05   238.6980.7025
   244.2   983.4   251.7  985.61   255.1  987.64   261.5  993.03   272.7 1003.86
   290.6 1016.94   309.2 1028.46   325.5 1034.91   330.1 1035.63   360.4 1035.74
   369.6 1041.51   384.5 1048.26   397.5 1057.68   404.2 1061.19   431.7 1071.09
#Mann= 3 ,-1,0
       0      .1       0  208.27    .045       0   238.6      .1       0
Bank Sta=208.27,238.6
XS Rating Curve= 0 ,0
Exp/Cntr(USF)=0,0
Exp/Cntr=0.3,0.1

Type RM Length L Ch R = 1 ,21817   ,211.2,205.8,197.7
XS GIS Cut Line= 6
 1652930.2470875449545.2284807611652992.11933909449483.356885334
1653045.15204141449430.3238549281653115.19323992449358.943420251
1653164.20035975449301.8844792591653220.36789834449234.308498924
#Sta/Elev= 30
       0 1025.81    10.9 1020.89    23.7 1012.83    32.9 1009.55    51.5  997.36
    60.8  993.01    65.4  991.72    88.6  989.28   123.5  988.08   166.4   984.3
   191.9  983.03   201.2  981.84  205.97979.7282   208.8  978.58   215.1  978.03
   224.4  978.23  233.12979.7302   240.2  981.68   254.3   982.4   259.2     984
   268.5  989.98   282.4 1002.64   293.9 1010.96   339.3 1027.88   354.5 1034.76
   380.1 1036.28   390.6  1042.6   401.2 1047.55   418.5 1058.83   425.6  1062.2
#Mann= 3 ,-1,0
       0      .1       0  205.97    .045       0  233.12      .1       0
Bank Sta=205.97,233.12
XS Rating Curve= 0 ,0
Exp/Cntr(USF)=0,0
Exp/Cntr=0.3,0.1

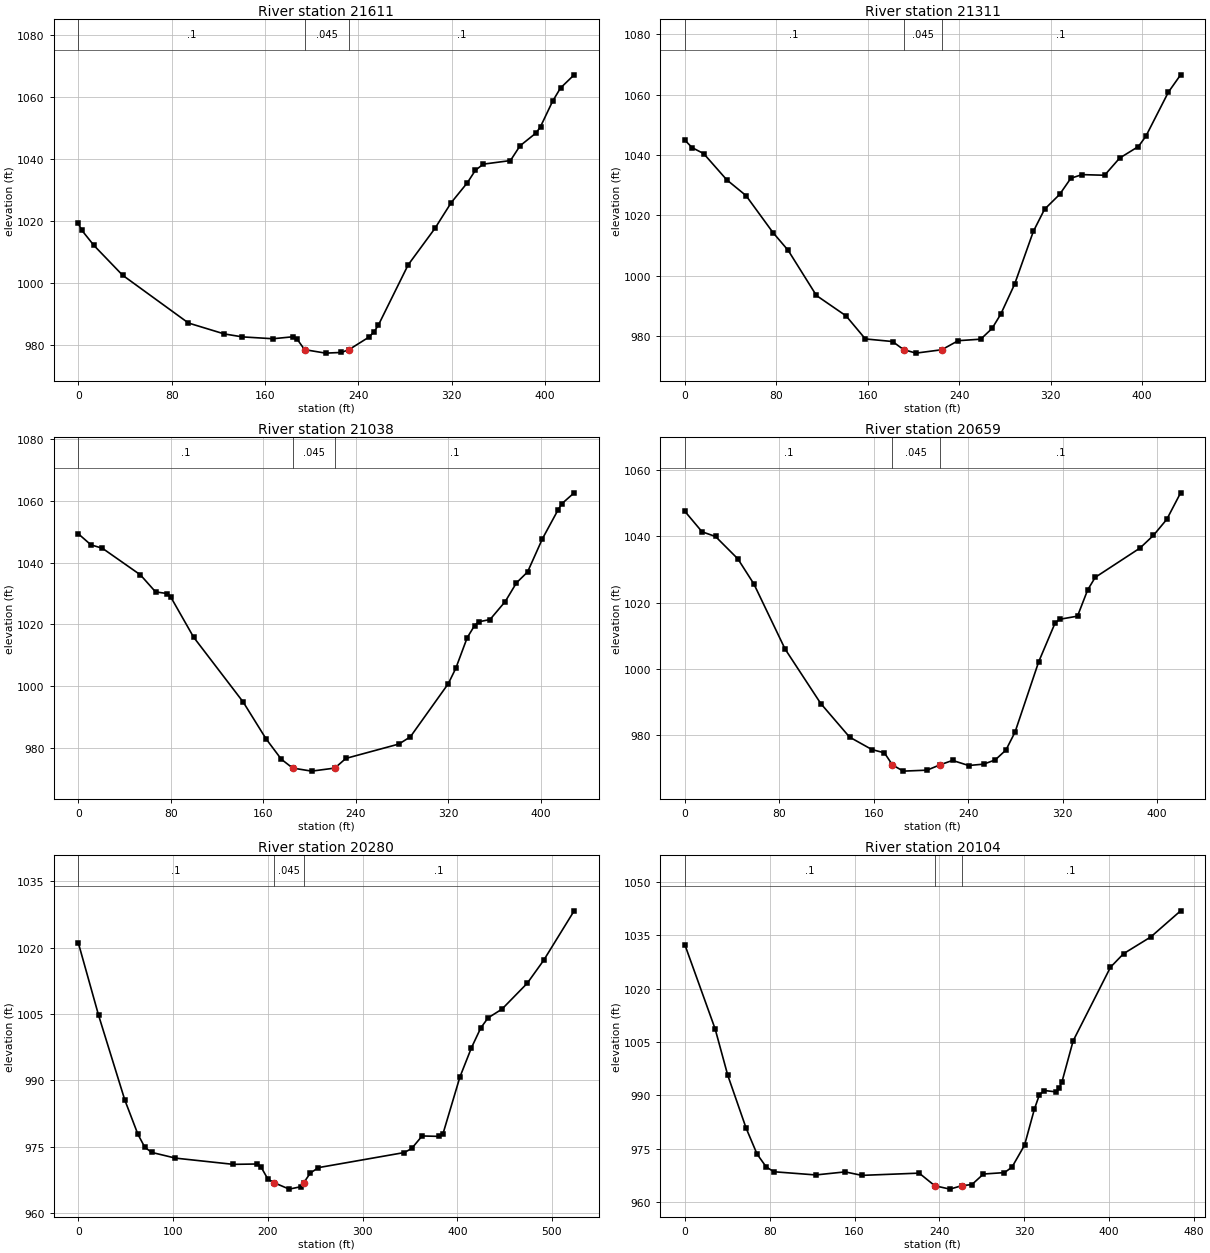
Type RM Length L Ch R = 1 ,21611   ,300.7,299.8,298.8
XS GIS Cut Line= 6
1653194.22628784449682.1412879231653224.78331333449600.125047758
1653249.31640075449529.2508456711653282.02729334449434.752347007
1653306.56038076449363.8784729991653335.18269885 449281.19228667
#Sta/Elev= 30
       0 1019.21     2.9 1017.06    13.4 1012.12    37.9 1002.54    94.4   987.1
   125.1  983.58   140.6  982.63   166.8  982.03   184.1  982.67   187.6  981.86
  193.93978.5203   211.9  977.39   225.5  977.61  232.01978.5227   249.2  982.58
   253.6  984.34   257.1  986.36   282.7 1005.86   305.7 1017.65   319.5 1025.88
   333.4 1032.33   340.4 1036.41   347.2 1038.36   370.4 1039.51   378.6 1044.27
   392.5 1048.46   396.2 1050.48   406.5 1058.63   413.3 1062.92     425 1067.17
#Mann= 3 ,-1,0
       0      .1       0  193.93    .045       0  232.01      .1       0
Bank Sta=193.93,232.01
XS Rating Curve= 0 ,0
Exp/Cntr(USF)=0,0
Exp/Cntr=0.3,0.1

Type RM Length L Ch R = 1 ,21311   ,276.1,273.3,269
XS GIS Cut Line= 4
1653492.90279308449800.4758622221653526.64383853449652.950873978
1653546.90646025449579.1370377191653551.62695602449373.478332629
#Sta/Elev= 30
       0 1044.91     6.4 1042.41    16.5 1040.44    36.7 1031.75    53.5 1026.55
    77.1  1014.3    90.4  1008.4   115.1  993.46     141  986.72   157.9  979.08
   181.7  978.22191.2638975.5609   202.1  974.38 224.712975.4988   239.1   978.5
   258.8     979   268.7  982.55   276.3  987.27   288.4  997.18   304.8 1014.67
   314.6 1022.01   327.8 1026.93   337.6 1032.28   347.4 1033.48   367.1 1033.27
   380.3 1038.96   396.7 1042.79   403.2 1046.18   422.9 1060.79   433.6 1066.52
#Mann= 3 ,-1,0
       0      .1       0191.2638    .045       0 224.712      .1       0
Bank Sta=191.2638,224.712
XS Rating Curve= 0 ,0
Exp/Cntr(USF)=0,0
Exp/Cntr=0.3,0.1

Type RM Length L Ch R = 1 ,21038   ,360.6,378.9,380.4
XS GIS Cut Line= 6
1653814.16160691449818.2424497831653807.56385107 449727.70522929
 1653799.5691164 449652.657479131653802.24922915449552.692127876
1653801.92541091449477.6424092131653800.90080665449390.063844212
#Sta/Elev= 30
       0 1049.39    10.9 1045.81    20.8 1044.71    53.7 1036.08    66.8 1030.57
    76.7 1030.04      80 1028.87    99.7  1015.9   142.6  994.87   162.4  982.93
   175.6  976.33   185.4  973.47   201.8  972.48  221.91  973.47   231.4   976.6
   277.3  981.26   287.2  983.59     320 1000.81   326.5 1005.79   336.4 1015.75
   342.7  1019.6   346.2 1020.86   356.1  1021.6   369.3 1027.45     379  1033.5
   388.6 1037.03   401.5 1047.83   415.1 1057.23   418.4  1059.2   428.9 1062.67
#Mann= 3 ,-1,0
       0      .1       0   185.4    .045       0  221.91      .1       0
Bank Sta=185.4,221.91
XS Rating Curve= 0 ,0
Exp/Cntr(USF)=0,0
Exp/Cntr=0.3,0.1

Type RM Length L Ch R = 1 ,20659   ,375.8,378.9,370.1
XS GIS Cut Line= 2
1654019.93089759449925.0188930181654228.99160676449560.990611583
#Sta/Elev= 30
       0 1047.64    14.6 1041.42      26    1040    44.9 1033.24    58.5 1025.63
    84.9 1005.95   115.1  989.47   139.5  979.31   158.4  975.54     169  974.54
   175.8  970.89   184.9  969.01   205.1   969.3  215.97   970.9   226.7  972.25
   240.3  970.71     253  971.12   262.8   972.4   271.9  975.39   279.6  980.82
   299.6 1002.07   313.5 1013.81   317.3 1014.94   332.5  1015.9   341.1 1023.84
   347.5 1027.64   385.4  1036.5   396.7  1040.3   408.1  1045.2   419.8 1053.21
#Mann= 3 ,-1,0
       0      .1       0   175.8    .045       0  215.97      .1       0
Bank Sta=175.8,215.97
XS Rating Curve= 0 ,0
Exp/Cntr(USF)=0,0
Exp/Cntr=0.3,0.1

Type RM Length L Ch R = 1 ,20280   ,171.6,176.6,176.9
XS GIS Cut Line= 3
1654349.19691322450048.5566163561654463.29269646449793.465123331
1654354.51378096449575.108702839
#Sta/Elev= 30
       0 1021.07    21.4 1004.69    49.1  985.53    62.9   977.8    70.1   974.9
    77.3  973.72   102.5  972.42   163.6  971.01   188.7  971.09   192.8  970.43
   200.2  967.64  206.28966.8952   222.6  965.41     235  965.96  238.07966.8966
   244.9  969.04   253.4  970.27   344.1  973.68   351.9   974.6   362.9  977.43
   381.2  977.33   384.9   977.9   402.8  990.76     415  997.38   424.8 1001.84
   432.5 1004.12   447.2  1006.1   473.8 1011.93   491.2 1017.13   523.4 1028.32
#Mann= 3 ,-1,0
       0      .1       0  206.28    .045       0  238.07      .1       0
Bank Sta=206.28,238.07
XS Rating Curve= 0 ,0
Exp/Cntr(USF)=0,0
Exp/Cntr=0.3,0.1

Type RM Length L Ch R = 1 ,20104   ,208.8,217.2,221.6
XS GIS Cut Line= 3
1654457.15299299450126.3856011861654632.92341912449864.494119301
1654727.91325229449745.910595021
#Sta/Elev= 30
       0  1032.4    28.6 1008.66    40.5  995.62    57.8  980.75    68.1  973.46
    76.7  969.86    83.9  968.49   123.4  967.59   151.1  968.45   166.9  967.47
   220.9   968.1   235.6  964.55   249.9   963.6  260.86  964.55   270.6  964.89
   281.5  967.85   301.3  968.25   308.4   969.8   320.2  975.97   329.5  986.12
   334.2  990.15   338.9  991.34   350.2  990.95   352.9  992.07   355.5  993.81
     366 1005.31   401.2 1026.03   413.5 1029.83   439.2 1034.55   467.3 1041.89
#Mann= 3 ,-1,0
       0      .1       0   235.6    .045       0  260.86      .1       0
Bank Sta=235.6,260.86
XS Rating Curve= 0 ,0
Exp/Cntr(USF)=0,0
Exp/Cntr=0.3,0.1

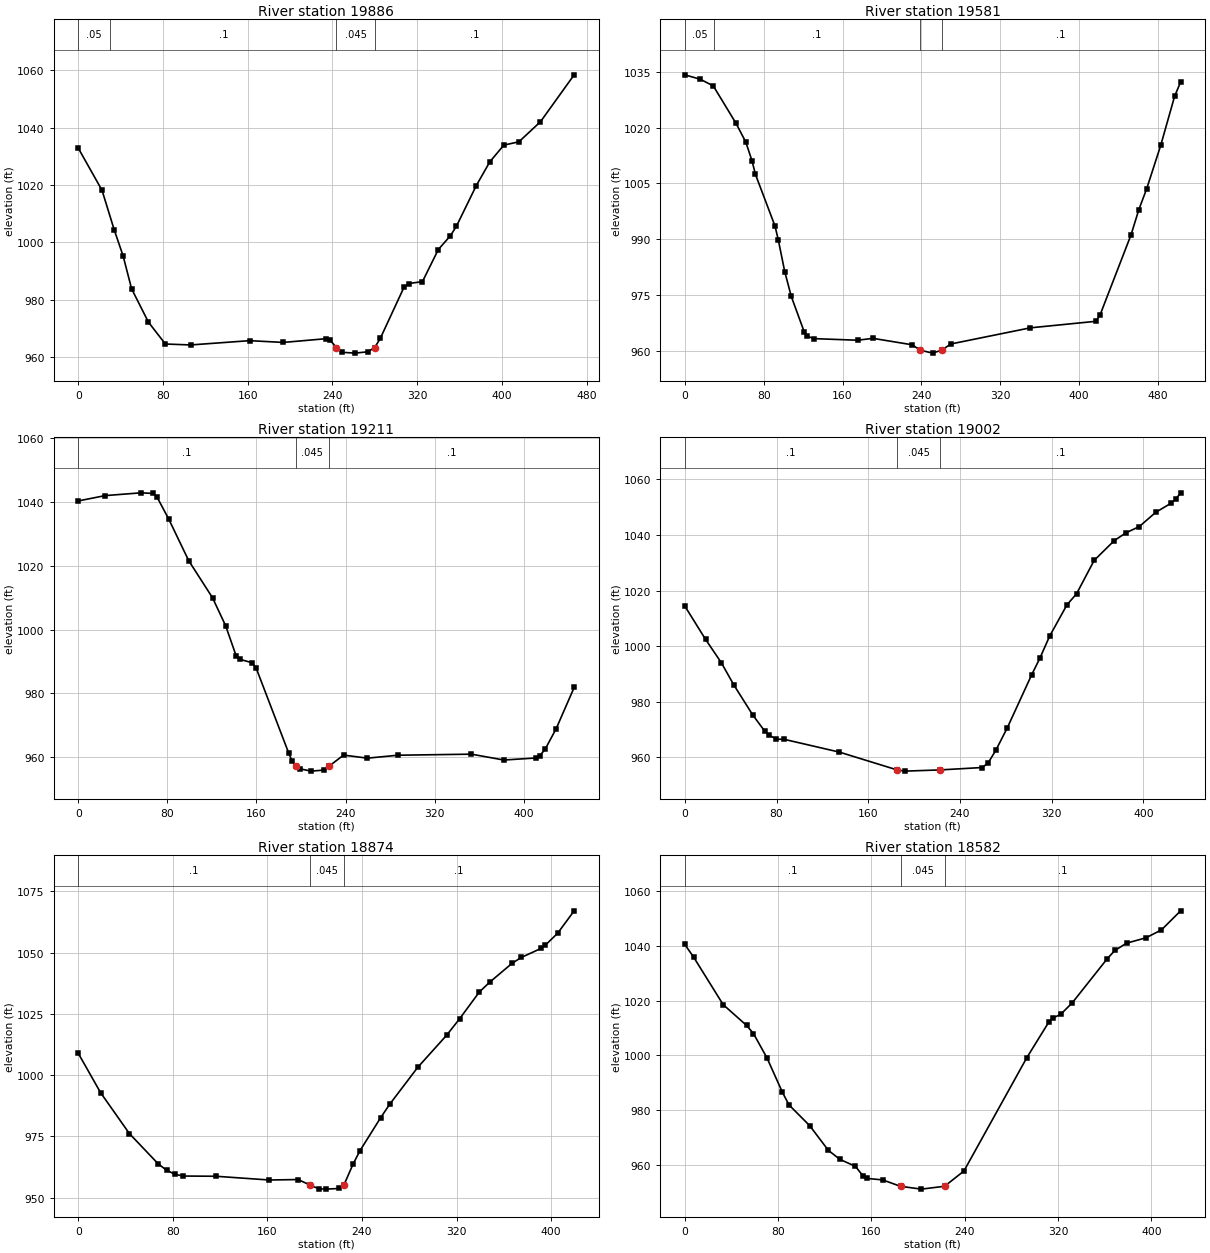
Type RM Length L Ch R = 1 ,19886   ,289.1,305.6,322.3
XS GIS Cut Line= 2
 1654544.3429311450200.1273920871654930.23569962449934.762154378
#Sta/Elev= 30
       0 1032.86    22.4 1018.17    33.9 1004.39    42.3   995.3    50.3  983.85
    66.2  972.22    82.2  964.59     106  964.26   161.8  965.76   193.6  965.14
   233.5  966.43   237.4  966.12   243.8  963.34   249.4  961.69   261.3  961.41
   273.3  961.87  279.88  963.34   285.2  966.55   307.5  984.31   312.2  985.69
     325  986.34     340  997.54   351.5 1002.38   357.1 1005.66   375.9 1019.86
   388.7 1028.15   401.9 1033.95   416.1  1035.1   436.5 1042.11   468.3 1058.46
#Mann= 4 ,-1,0
       0     .05       0      30      .1       0   243.8    .045       0
  279.88      .1       0
Bank Sta=243.8,279.88
XS Rating Curve= 0 ,0
Exp/Cntr(USF)=0,0
Exp/Cntr=0.3,0.1

Type RM Length L Ch R = 1 ,19581   ,376.7,369.4,366.9
XS GIS Cut Line= 3
1654540.59892318450237.3284977531654687.91699323450250.683193946
1654981.75353634450449.975623788
#Sta/Elev= 30
       0 1034.21    15.7 1033.02    28.9 1031.23      52 1021.15    61.9 1016.11
    68.2 1011.07    71.7 1007.42    91.5  993.54    94.8  989.88   101.4  981.27
     108  974.62   121.1  965.12   124.4  963.88     131  963.26   175.2  962.83
     191  963.33   230.7   961.6   238.6  960.18   251.3  959.36   260.7  960.17
   269.9  961.82   350.5  966.16     417  967.92   421.3  969.65   452.7  991.18
   460.6  997.95   468.5 1003.52   482.8 1015.23   496.9 1028.44     503 1032.29
#Mann= 4 ,-1,0
       0     .05       0      30      .1       0   238.6    .045       0
   260.7      .1       0
Bank Sta=238.6,260.7
XS Rating Curve= 0 ,0
Exp/Cntr(USF)=0,0
Exp/Cntr=0.3,0.1

Type RM Length L Ch R = 1 ,19211   ,217.9,209.5,202.3
XS GIS Cut Line= 6
  1654337.228595450463.914330676 1654417.6539591450498.381781429
1654486.58951676450527.9266698361654578.65494943450566.966618001
1654655.15184367450591.0899293421654748.30257601450634.049161002
#Sta/Elev= 30
       0 1040.36    24.1 1042.03    56.3  1042.9      67 1042.71    70.5 1041.68
    81.3 1034.59    99.1 1021.64   120.5    1010   132.3 1001.21   141.9  991.61
   145.5  990.65   156.2  989.59   159.8  987.85     189  961.22   191.9  958.85
  195.18957.1666     199  956.34   209.1  955.62   220.4  955.94  225.17957.1686
   238.2  960.65   259.6  959.69   287.2  960.61     353  960.94   382.2   959.1
   410.8  959.74   414.5  960.47   419.3  962.52   429.2  968.97   445.3  981.86
#Mann= 3 ,-1,0
       0      .1       0  195.18    .045       0  225.17      .1       0
Bank Sta=195.18,225.17
XS Rating Curve= 0 ,0
Exp/Cntr(USF)=0,0
Exp/Cntr=0.3,0.1

Type RM Length L Ch R = 1 ,19002   ,118.5,128.1,134.4
XS GIS Cut Line= 6
1654348.68538307450712.7314506371654500.28280712450759.701278804
1654519.67836161450756.6395929511654573.20005096450749.956985092
1654598.29876334450741.4515607991654743.86231026450836.238943718
#Sta/Elev= 30
       0 1014.41    18.1 1002.41    31.8  994.05    42.8  985.97    59.3  975.17
    69.6  969.43    73.1  968.01    79.9  966.48    86.8   966.4   134.9   961.8
   185.5  955.36   192.1  954.96   222.7955.3991   259.5  956.26   264.7  957.99
   271.3  962.46   281.3  970.55   302.6  989.69   309.7   995.6   318.2 1003.54
   333.4 1014.88   341.7 1018.81   357.1 1030.86   374.7    1038   384.8 1040.77
   396.5 1043.04   410.8 1048.16     424  1051.4   428.3 1052.92   432.5 1055.18
#Mann= 3 ,-1,0
       0      .1       0   185.5    .045       0   222.7      .1       0
Bank Sta=185.5,222.7
XS Rating Curve= 0 ,0
Exp/Cntr(USF)=0,0
Exp/Cntr=0.3,0.1

Type RM Length L Ch R = 1 ,18874   ,296.5,291.4,289.8
XS GIS Cut Line= 2
1654328.58064643450807.2837226691654723.67072668450948.407200823
#Sta/Elev= 30
       0 1008.87    18.8  992.89    43.2  976.18    67.6  963.82    74.6  961.25
    81.5  959.63    88.5  958.86   116.4  958.77   161.6  957.24     186  957.43
  196.02955.1856   203.5  953.65   209.5  953.52   220.9  953.79  224.68955.1812
   232.6  963.89   238.3   969.2   255.7   982.6   263.4  988.11   287.1 1003.16
   311.5 1016.24   322.5 1022.95   339.3 1033.94   348.1 1037.95   367.2 1045.72
   374.9 1048.05   391.6 1051.73   395.1 1053.03   405.5 1057.88   419.5 1067.04
#Mann= 3 ,-1,0
       0      .1       0  196.02    .045       0  224.68      .1       0
Bank Sta=196.02,224.68
XS Rating Curve= 0 ,0
Exp/Cntr(USF)=0,0
Exp/Cntr=0.3,0.1

Type RM Length L Ch R = 1 ,18582   ,273.7,271.3,267.9
XS GIS Cut Line= 6
1654232.11207642451118.1335248691654317.82483151451136.365771879
1654391.92573317451147.9448169661654490.72704475451163.382450123
1654564.82794642451174.9608390371654651.19391542451189.013304372
#Sta/Elev= 30
       0 1040.53     7.5 1035.96    32.9 1018.55      53 1010.94    58.9 1007.97
    70.5  999.05    83.7  986.51    89.3  981.93   107.1  974.32   123.1   965.3
     133  962.01   146.3  959.46     153  955.85   156.3  955.05   169.6  954.51
  184.95  952.17   202.8  951.14   222.7  952.18   239.3  957.75   293.2  999.15
   312.4 1012.39   315.7 1013.67   322.3 1015.01   332.3 1019.27   362.2 1035.34
   368.8 1038.38   378.8 1041.02   395.4 1042.97   408.7 1045.88   425.1 1052.83
#Mann= 3 ,-1,0
       0      .1       0  184.95    .045       0   222.7      .1       0
Bank Sta=184.95,222.7
XS Rating Curve= 0 ,0
Exp/Cntr(USF)=0,0
Exp/Cntr=0.3,0.1