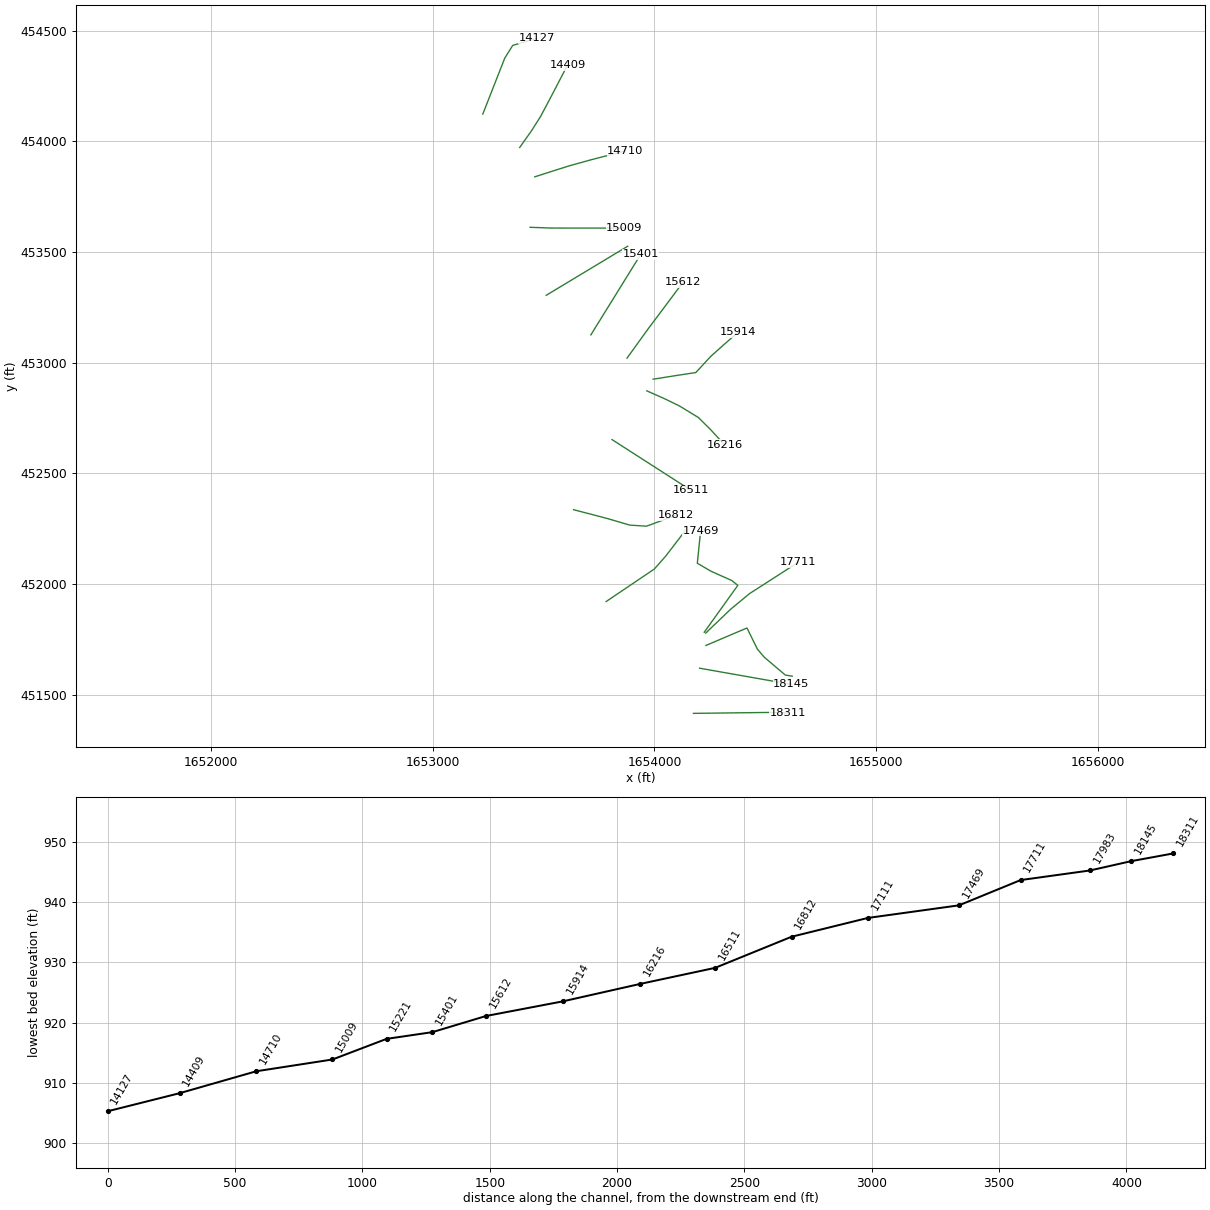
HEC-RAS study LaurelRnI.prj: LaurelRnI

--- LaurelRnI.g01 (geometry) --- (continued)

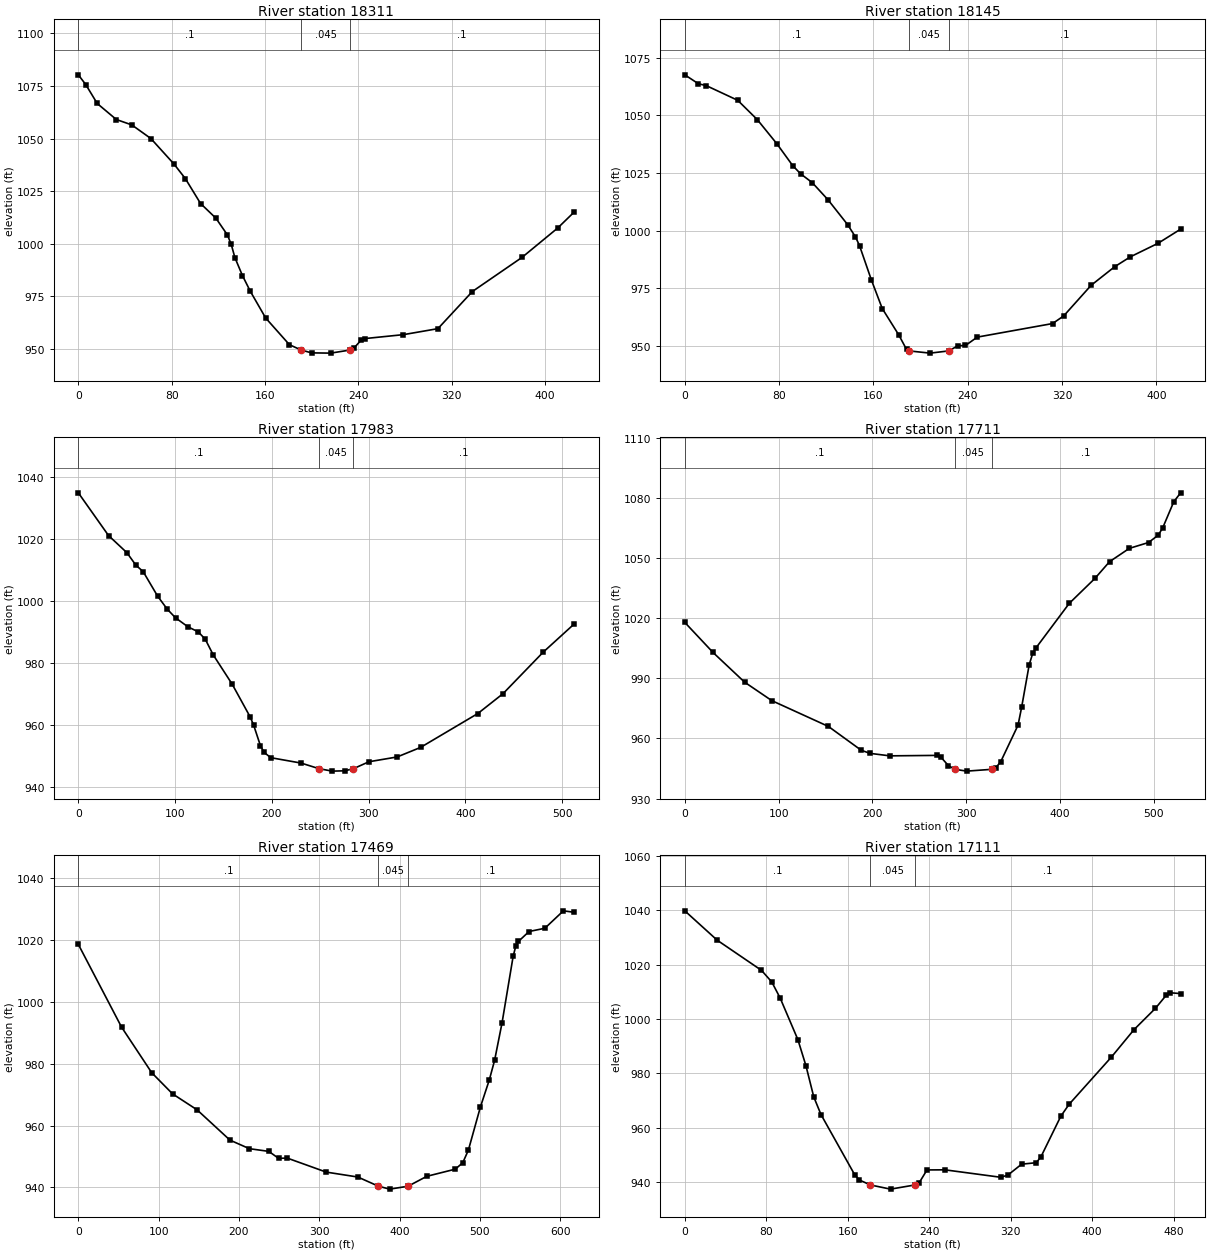
Type RM Length L Ch R = 1 ,18311   ,170.4,166.5,162.9
XS GIS Cut Line= 6
1654175.85621434451416.6565196661654263.34947768451417.764129013
1654338.34342217 451418.713602171654438.33534817451419.979347676
1654513.33093309451420.7966032621654600.86159793451418.923575506
#Sta/Elev= 30
       0  1080.3     6.4 1075.64    16.2 1066.68    32.6 1059.06    45.8 1056.52
    62.2 1050.03    81.9 1037.99    91.7 1031.04   104.8 1019.16     118 1012.16
   127.8 1004.25   131.1  999.73   134.2  993.51   140.7  984.92   147.5  977.41
   160.6  964.78     181  952.07   191.1949.5469     200   948.2   216.4  948.08
  232.95949.5486   236.1  950.36   242.6  954.34   245.9  955.01   278.7  956.86
   308.3  959.71   337.8  977.34   380.4  993.56     411 1007.52   425.1  1015.1
#Mann= 3 ,-1,0
       0      .1       0   191.1    .045       0  232.95      .1       0
Bank Sta=191.1,232.95
XS Rating Curve= 0 ,0
Exp/Cntr(USF)=0,0
Exp/Cntr=0.3,0.1

Type RM Length L Ch R = 1 ,18145   ,178,161.4,149.8
XS GIS Cut Line= 2
 1654203.6739504451620.6719661971654617.82507121451547.522838694
#Sta/Elev= 30
       0 1067.56    11.6 1063.67    18.2 1062.88    44.9  1056.5    61.5 1048.12
    78.2 1037.58    91.5 1028.19    98.2 1024.62   108.1 1020.78   121.5 1013.33
   138.2  1002.5   144.8   997.2   148.2  993.46   158.2  978.65   167.5  966.14
   181.5   954.7   188.1  948.38  189.94  947.77   208.1  946.79   224.2  947.77
   231.5  949.99   238.1  950.11   248.1  953.74     312  959.63   321.4  962.93
   344.7  976.23   364.7   984.3     378  988.59   401.4  994.44   420.6 1000.59
#Mann= 3 ,-1,0
       0      .1       0  189.94    .045       0   224.2      .1       0
Bank Sta=189.94,224.2
XS Rating Curve= 0 ,0
Exp/Cntr(USF)=0,0
Exp/Cntr=0.3,0.1

Type RM Length L Ch R = 1 ,17983   ,232.4,272.1,291.2
XS GIS Cut Line= 6
  1654232.274193451723.3481896341654417.46221138 451802.28771336
1654464.15725467451707.222229281  1654495.516074451670.234903922
1654590.39660427451589.8276748811654621.65300691 451584.52106421
#Sta/Elev= 30
       0 1035.04    31.2 1021.26    50.2 1015.72    59.4 1011.72      67 1009.61
    81.9 1001.72    91.9  997.49   100.4  994.72   113.2  991.82   123.9  990.18
   131.1  987.83   139.4  982.74     159  973.28   177.4  962.82     181  960.22
   188.1   953.5   191.9  951.31   198.8  949.59   230.3  947.84   248.7  946.04
   262.3  945.25   275.1  945.35   283.9  945.99   300.3  948.28   329.4  949.82
   353.6   952.9   412.8  963.84   438.8  970.24   480.3  983.63   512.3  992.72
#Mann= 3 ,-1,0
       0      .1       0   248.7    .045       0   283.9      .1       0
Bank Sta=248.7,283.9
XS Rating Curve= 0 ,0
Exp/Cntr(USF)=0,0
Exp/Cntr=0.3,0.1

Type RM Length L Ch R = 1 ,17711   ,210.2,242.2,280.9
XS GIS Cut Line= 6
1654231.34986976451779.351332337 1654343.7643431451886.886222258
1654428.83831993451957.3286666721654512.91000217 452011.47619617
1654575.96368185452052.0870073441654649.52652684452099.465849593
#Sta/Elev= 30
       0 1017.84    30.1 1002.84    63.7  988.05    92.7  978.83   153.1  965.94
     188  954.09   197.3  952.53   218.5  951.28   269.3  951.51   273.2   950.5
     281  946.41  287.89 944.562   300.5  943.66   327.3944.5625   331.7  945.45
   336.8  948.42   355.2  966.58   359.1   975.7   367.1  996.73   370.8 1002.34
   374.1 1004.98   409.8 1027.34   437.1 1039.75   452.7 1048.11   473.8 1054.76
   494.3 1057.69   504.6 1061.34   509.4 1064.99   521.2 1078.02   528.5 1082.47
#Mann= 3 ,-1,0
       0      .1       0  287.89    .045       0   327.3      .1       0
Bank Sta=287.89,327.3
XS Rating Curve= 0 ,0
Exp/Cntr(USF)=0,0
Exp/Cntr=0.3,0.1

Type RM Length L Ch R = 1 ,17469   ,398.1,357.8,317.9
XS GIS Cut Line= 6
1654224.60553536451783.0788669751654376.13034097451994.753157404
1654348.37084485452016.7900610891654255.09845916452058.601820191
1654193.37523646452094.6200169081654208.36443289   452241.935709
#Sta/Elev= 30
       0 1018.49    53.8   991.8    91.4  977.06   117.3  970.24   147.9  965.07
   188.8   955.3     213  952.53   237.2  951.66   249.3  949.43   260.3  949.48
   308.7  944.97   348.1  943.38   373.7  940.42   387.8  939.47   410.6   940.4
     434  943.61   469.5  945.92   478.8  948.01   485.8  952.09   500.7  965.96
   511.8  974.71   518.4  981.03   527.7  993.17   541.5 1014.63   544.8 1017.93
   548.1 1019.45   561.3 1022.65     581  1023.7   604.1 1029.33   617.5 1028.86
#Mann= 3 ,-1,0
       0      .1       0   373.7    .045       0   410.6      .1       0
Bank Sta=373.7,410.6
XS Rating Curve= 0 ,0
Exp/Cntr(USF)=0,0
Exp/Cntr=0.3,0.1

Type RM Length L Ch R = 1 ,17111   ,314.8,299.7,284.2
XS GIS Cut Line= 6
1653781.88948259 451921.649932251653854.41427192451970.603574499
 1653916.5781896452012.5637924221653999.46319443452068.510530919
1654050.78494218452126.8936162591654139.97013126  452243.2368875
#Sta/Elev= 30
       0 1039.75    31.8 1028.95    75.3 1017.85    85.4 1013.58    93.6 1007.69
     111   992.4   118.9  982.83   126.6  971.32   133.7  964.82   166.8  942.67
   171.5  940.73  182.19938.9115     202  937.38  225.92938.9112   229.7  939.48
   237.8  944.44   255.4  944.48   310.2  941.74   317.2  942.54   330.7  946.56
   345.1   947.1   349.8  949.37   369.2  964.22   377.4  968.62   418.8  985.94
     441  996.03   462.1  1003.9   472.5 1008.63   476.7 1009.61   486.8  1009.3
#Mann= 3 ,-1,0
       0      .1       0  182.19    .045       0  225.92      .1       0
Bank Sta=182.19,225.92
XS Rating Curve= 0 ,0
Exp/Cntr(USF)=0,0
Exp/Cntr=0.3,0.1

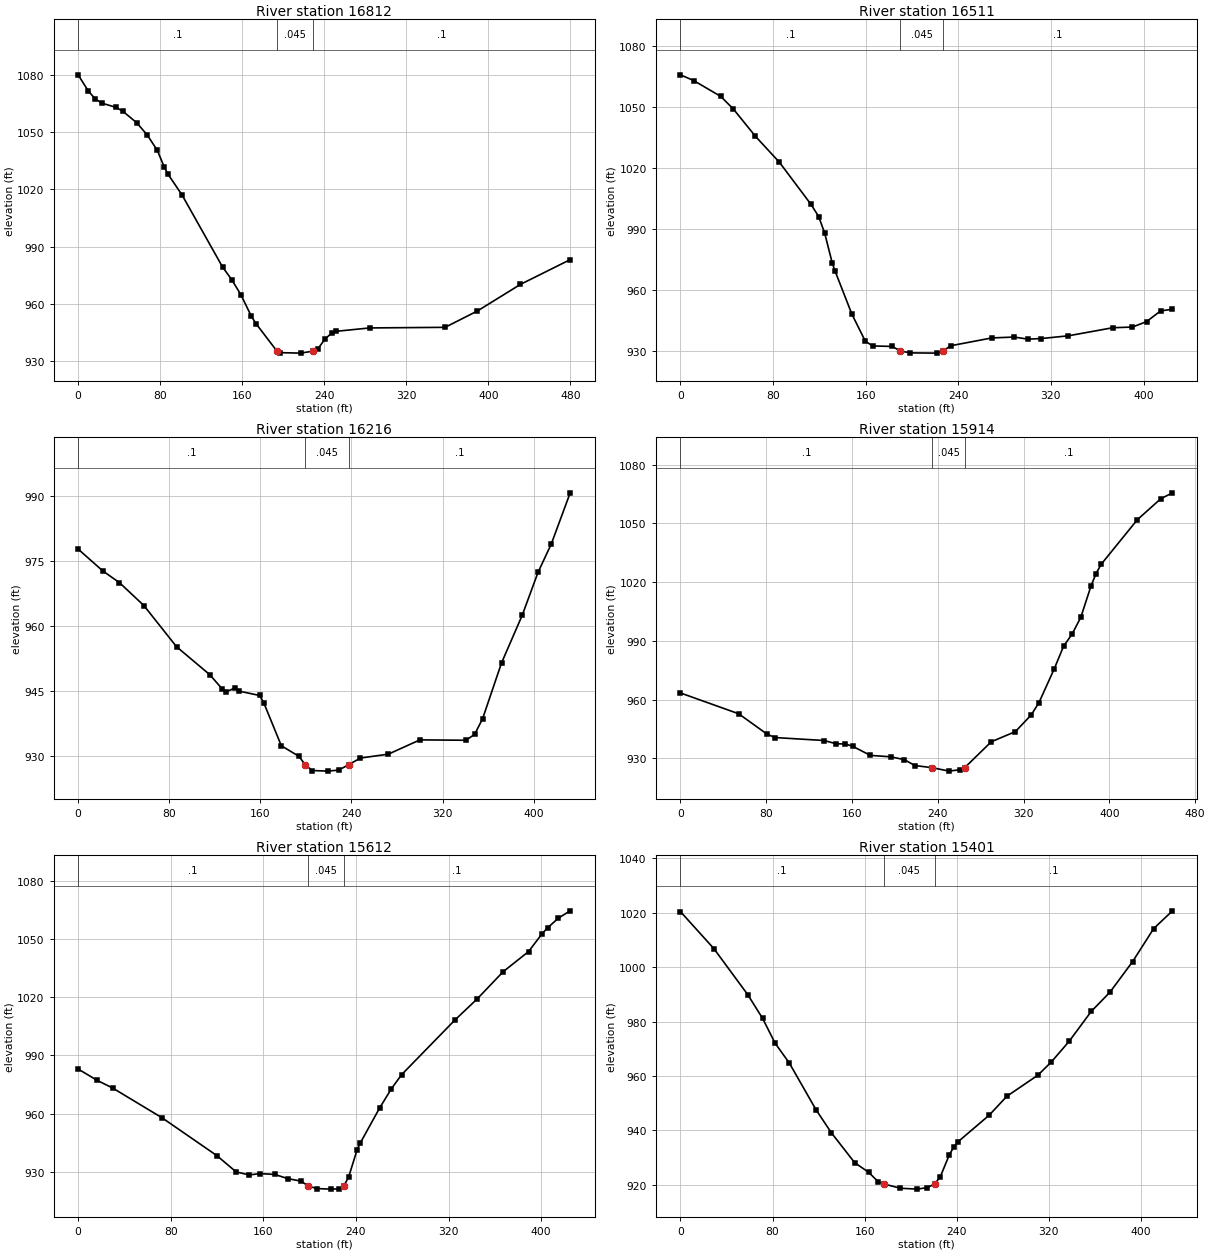
Type RM Length L Ch R = 1 ,16812   ,305.3,300.3,295.5
XS GIS Cut Line= 6
1653634.92947467 452336.319378511653719.71998751452314.425393417
1653792.26249334452295.213161498  1653888.178312452266.919911012
 1653963.9950895 452262.017361761654096.57520492 452310.79876025
#Sta/Elev= 30
       0 1079.88     9.6 1071.67    16.4 1067.37    23.1 1065.06    36.7  1062.9
    43.5 1060.86      57 1054.86    67.2 1048.54    77.2 1040.39    84.1 1031.48
    87.5 1028.01   101.4 1016.96   140.9  979.27   149.7  972.78   158.8  964.76
     169  953.47   173.6   949.6  193.96935.2607   196.4  934.52   216.9  934.26
  228.74935.2594     234   936.6   240.8  941.69   247.6  944.88   251.1  945.65
   284.4  947.44   357.9  947.76   389.4  956.31   431.3   970.2   479.9  983.18
#Mann= 3 ,-1,0
       0      .1       0  193.96    .045       0  228.74      .1       0
Bank Sta=193.96,228.74
XS Rating Curve= 0 ,0
Exp/Cntr(USF)=0,0
Exp/Cntr=0.3,0.1

Type RM Length L Ch R = 1 ,16511   ,295.3,295.2,296.2
XS GIS Cut Line= 6
1653808.50852384452652.984755665  1653882.111395452605.668249249
1653945.19985151452565.111571833 1654029.3177935452511.035564512
1654092.40592192452470.4785590021654166.00879309452423.161724508
#Sta/Elev= 30
       0 1065.64    11.4 1062.84    34.8 1055.05    45.8 1048.81    64.7 1035.53
    85.5 1022.73   112.8 1002.06   119.4  996.08   124.5  988.13   131.2  973.16
   133.6   969.3   148.1   948.2   159.7  934.95     166  932.63     183  932.38
  189.75 930.181   198.6  929.22   221.4   929.1  226.68930.1824   233.7  932.75
   268.9  936.55   288.3  936.99     300  935.96   311.6  936.25   335.1   937.6
   373.4  941.56   390.4  941.89   402.6  944.55   414.7  949.81     425  950.63
#Mann= 3 ,-1,0
       0      .1       0  189.75    .045       0  226.68      .1       0
Bank Sta=189.75,226.68
XS Rating Curve= 0 ,0
Exp/Cntr(USF)=0,0
Exp/Cntr=0.3,0.1

Type RM Length L Ch R = 1 ,16216   ,286.1,302.3,327
XS GIS Cut Line= 6
1653965.44357742452873.1250634191654045.49262993452837.654333845
1654112.93508033452804.844032004  1654198.630447452752.406144753
1654253.96859093452697.333420262 1654315.5399901452630.476270512
#Sta/Elev= 30
       0  977.64    21.8  972.57    36.2  969.92    57.7  964.63    86.4  955.12
   115.6  948.67   126.5  945.38   130.2  944.76   137.4  945.57   141.1  944.89
   159.4  943.88   163.1  942.12   178.4  932.28   193.8  929.85  199.42927.9124
   205.4  926.57   219.3  926.43   228.8  926.67  237.48927.9135   247.9  929.45
   272.3  930.34   300.1  933.64   340.5  933.55   348.1  934.91   355.1  938.51
   371.7  951.37   389.9  962.39   403.8   972.3   415.4  978.81     432  990.62
#Mann= 3 ,-1,0
       0      .1       0  199.42    .045       0  237.48      .1       0
Bank Sta=199.42,237.48
XS Rating Curve= 0 ,0
Exp/Cntr(USF)=0,0
Exp/Cntr=0.3,0.1

Type RM Length L Ch R = 1 ,15914   ,300.4,302.1,303.4
XS GIS Cut Line= 6
1653994.11313951452925.8198399251654102.83175409 452943.04388684
1654186.51367334452955.7715516691654254.49418043 453029.29207392
 1654310.9809441 453079.827405931654377.47228092453137.879455179
#Sta/Elev= 30
       0  963.45    54.3  952.83    80.9  942.38    88.4  940.68     134  939.18
   145.2  937.52   153.9  937.41   160.5  936.26   177.1   931.6   196.3  930.84
   208.8  929.42   218.6  926.41  234.98925.2946   250.6  923.55   260.9  924.29
  265.08925.2941   289.9  938.53   312.4  943.72   327.2  952.27   334.4  958.54
   348.7  975.87   357.4  987.38   365.2  993.42   373.4 1002.06     383 1018.19
   387.6 1024.35   392.3 1029.05   426.2 1051.91     448 1062.57   458.9 1065.59
#Mann= 3 ,-1,0
       0      .1       0  234.98    .045       0  265.08      .1       0
Bank Sta=234.98,265.08
XS Rating Curve= 0 ,0
Exp/Cntr(USF)=0,0
Exp/Cntr=0.3,0.1

Type RM Length L Ch R = 1 ,15612   ,209.6,210.7,211.7
XS GIS Cut Line= 6
 1653876.0959871 453020.739269511653927.21530743453091.725019917
1653971.04395993453152.5851344171654031.01824942453232.621719763
1654076.01717517453292.6954185071654128.32645376453362.935107425
#Sta/Elev= 30
       0  982.98    16.2  977.21    29.9  973.16    72.6  957.82   119.7  938.44
   136.5     930   147.8  928.44   157.2  929.11     170  928.68     181  926.54
   192.7  925.23  198.76 922.682   206.4  921.41   218.1  921.12   225.5  921.27
  229.46 922.684   233.7  927.39   241.1  941.53   243.9  945.03   260.4  962.85
   270.6  972.78   279.4  980.03   325.7 1008.34   344.7 1019.05   367.1 1033.06
   389.1 1043.46   400.9 1052.72   405.7 1055.75     415 1060.76   425.1 1064.46
#Mann= 3 ,-1,0
       0      .1       0  198.76    .045       0  229.46      .1       0
Bank Sta=198.76,229.46
XS Rating Curve= 0 ,0
Exp/Cntr(USF)=0,0
Exp/Cntr=0.3,0.1

Type RM Length L Ch R = 1 ,15401   ,186.5,179.5,169.9
XS GIS Cut Line= 2
1653712.96499331453125.8858763691653938.02718034453489.379170493
#Sta/Elev= 30
       0 1020.41      29 1006.84    58.5  989.89    71.4  981.16    82.3  972.03
    94.6  964.77   117.7  947.68   131.1  939.16   151.4  928.15   163.4  924.67
   171.7  921.21   176.9  920.32     191  918.77   205.9  918.44   214.2     919
  220.95  920.31   225.8  923.01   233.5  930.94   237.3  933.79   241.2  935.85
   268.2  945.59   283.6  952.56   310.6  960.32   322.2  965.15   337.7  972.74
   356.9  983.73   373.1  990.76   392.9 1002.06   411.2 1014.19   427.5  1020.7
#Mann= 3 ,-1,0
       0      .1       0   176.9    .045       0  220.95      .1       0
Bank Sta=176.9,220.95
XS Rating Curve= 0 ,0
Exp/Cntr(USF)=0,0
Exp/Cntr=0.3,0.1

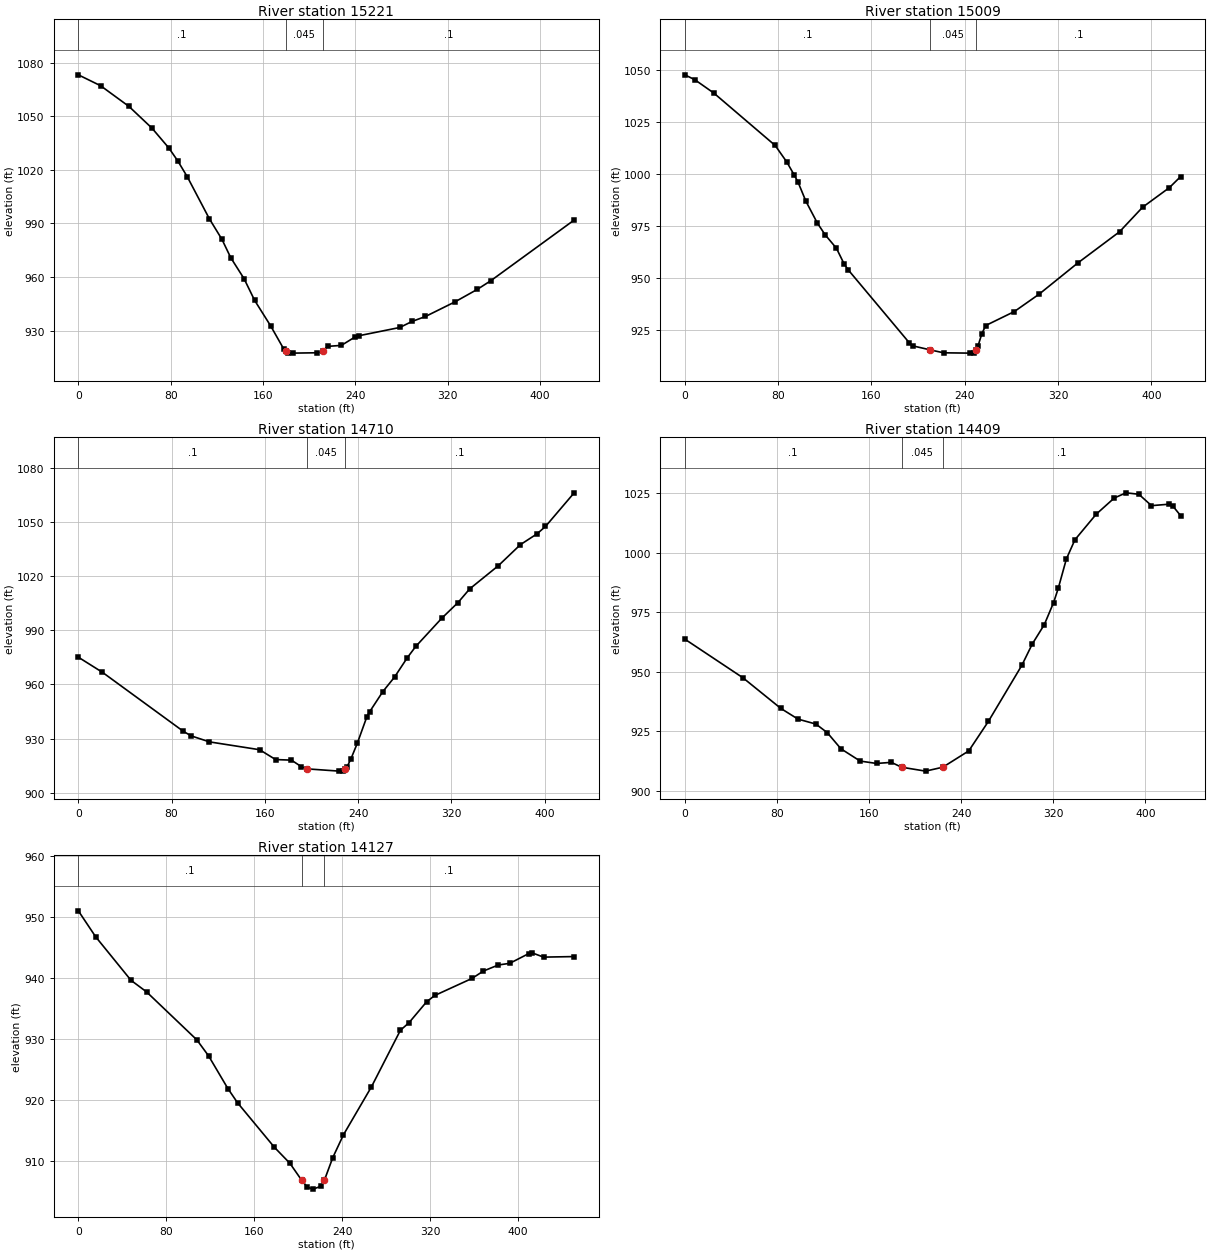
Type RM Length L Ch R = 1 ,15221   ,218.5,212.5,200.7
XS GIS Cut Line= 2
1653511.44437133 453304.597228441653879.22688635453526.292064175
#Sta/Elev= 30
       0 1073.24    19.3 1067.13    43.9 1055.51    63.8 1043.35    78.4 1032.25
    86.1 1025.03    94.4 1016.08   113.5  992.57   124.4  981.03     132  970.79
   143.5  959.06   152.7  946.86   166.5  932.65     178  919.52  179.51  918.61
   181.8  917.56   185.7  917.33   206.7  917.53   211.5   918.6   216.3  921.13
   227.8  921.67   239.3  926.24   243.1  927.09   278.4   931.7   289.1  935.11
   300.6  937.85   326.2  946.05   345.4     953   357.3  957.93   429.4  991.88
#Mann= 3 ,-1,0
       0      .1       0  179.51    .045       0   211.5      .1       0
Bank Sta=179.51,211.5
XS Rating Curve= 0 ,0
Exp/Cntr(USF)=0,0
Exp/Cntr=0.3,0.1

Type RM Length L Ch R = 1 ,15009   ,294.1,299,303
XS GIS Cut Line= 6
1653438.77894834453611.7164340021653526.27877334453608.572083339
1653601.27895142453608.2006930111653701.27907951453608.200693011
 1653776.2789295453608.200693011 1653863.7787545453608.200693011
#Sta/Elev= 30
       0 1047.57     8.6 1045.22      25 1038.76    77.5 1013.63    87.4 1005.74
    93.9  999.38    97.2  995.87   103.8  986.89   113.6  976.43   120.2  970.84
     130  964.28   136.6  956.74   139.9  954.04   192.4  918.93   195.6  917.38
  210.04915.5154   221.9  914.06   244.9  913.91   248.1     914  249.61915.5189
   251.4  917.38   254.7  923.28     258  927.17   282.6   933.9   303.9  942.28
   336.7   957.1   372.8  972.23   392.5  983.98   415.5  993.41   425.1  998.71
#Mann= 3 ,-1,0
       0      .1       0  210.04    .045       0  249.61      .1       0
Bank Sta=210.04,249.61
XS Rating Curve= 0 ,0
Exp/Cntr(USF)=0,0
Exp/Cntr=0.3,0.1

Type RM Length L Ch R = 1 ,14710   ,280.4,301.4,308.8
XS GIS Cut Line= 6
1653459.93441784453839.7271328421653543.40078634453866.465268344
1653615.02170609453889.0803805891653711.36567351453915.942531586
1653783.98659125453934.6833077521653868.71083125453956.547437251
#Sta/Elev= 30
       0  975.09    20.7   966.7    90.1     934    96.8  931.49   112.5  928.16
   155.5  923.82   169.2  918.37   182.8  918.05   191.4  914.38  195.98913.2175
   223.7  911.96   227.1  912.16  228.79913.2184   230.5  914.33   233.9  918.87
   239.4  927.57   247.5   942.1     250  944.98   261.2  956.03   271.2  964.04
   282.2  974.82   289.4  981.02   311.8  996.72   325.6 1005.31   335.7 1012.93
   360.3  1025.8   379.2 1037.45   393.3 1043.37   400.7 1047.51   425.3 1066.16
#Mann= 3 ,-1,0
       0      .1       0  195.98    .045       0  228.79      .1       0
Bank Sta=195.98,228.79
XS Rating Curve= 0 ,0
Exp/Cntr(USF)=0,0
Exp/Cntr=0.3,0.1

Type RM Length L Ch R = 1 ,14409   ,283.7,282,282.5
XS GIS Cut Line= 6
1653391.80266434453972.316434592  1653444.683136 454046.85434325
1653485.71914317454111.6478488451653532.62062417454199.971163005
1653567.22193292454266.5126965941653607.58996242454344.144103006
#Sta/Elev= 30
       0  963.72    50.5  947.49    83.4  934.64    98.3  930.15   113.9  928.06
   123.7  924.48   135.6  917.69   152.3  912.54   166.5  911.54   179.4     912
   188.2909.9727   209.1  908.32   224.1909.9728   246.6  916.81   263.6  929.15
   292.7  952.72   301.8   961.7   312.2  969.79   320.3  979.07   324.4  985.15
   331.4  997.38   338.8 1005.41   357.3 1016.15     373 1022.95   383.2 1025.11
   394.3 1024.51   405.3 1019.73   420.1 1020.32   424.1 1019.41   430.6 1015.53
#Mann= 3 ,-1,0
       0      .1       0   188.2    .045       0   224.1      .1       0
Bank Sta=188.2,224.1
XS Rating Curve= 0 ,0
Exp/Cntr(USF)=0,0
Exp/Cntr=0.3,0.1

Type RM Length L Ch R = 1 ,14127   ,188.6,181.1,174.9
XS GIS Cut Line= 4
1653225.33084889454122.9910889421653324.60609553454376.037771924
1653360.39371104454433.1463918581653467.46501921454465.046590526
#Sta/Elev= 30
       0  951.02    15.8  946.75    47.9  939.61      62  937.72   107.8  929.83
   118.4  927.22     136  921.84   144.9  919.48   178.3   912.2   192.4  909.57
  203.22  906.76   208.2  905.67   213.5  905.33   220.9  905.82223.7097906.7639
   231.4  910.51   241.1  914.25   266.6  922.14   292.9  931.41   300.7  932.65
   316.7  936.08   324.1  937.12   358.1  939.93   368.3  941.13     382  942.13
   392.3   942.4   409.4  943.98   412.8  944.11   423.1  943.42   450.9  943.51
#Mann= 3 ,-1,0
       0      .1       0  203.22    .045       0223.7097      .1       0
Bank Sta=203.22,223.7097
XS Rating Curve= 0 ,0
Exp/Cntr(USF)=0,0
Exp/Cntr=0.3,0.1