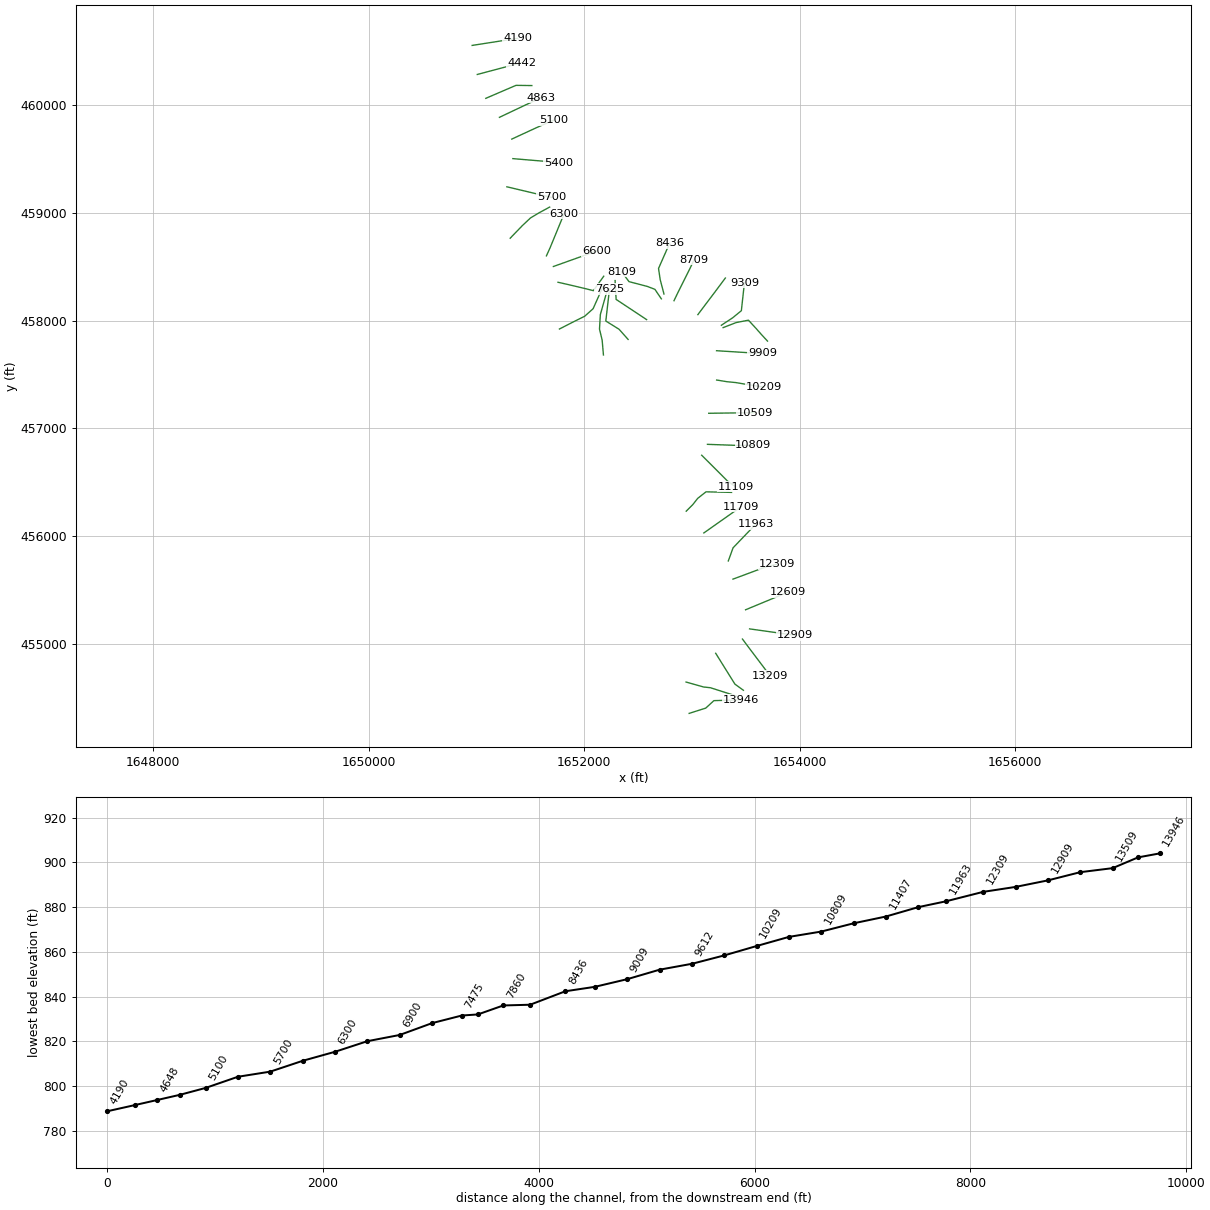
HEC-RAS study LaurelRnI.prj: LaurelRnI

--- LaurelRnI.g01 (geometry) --- (continued)

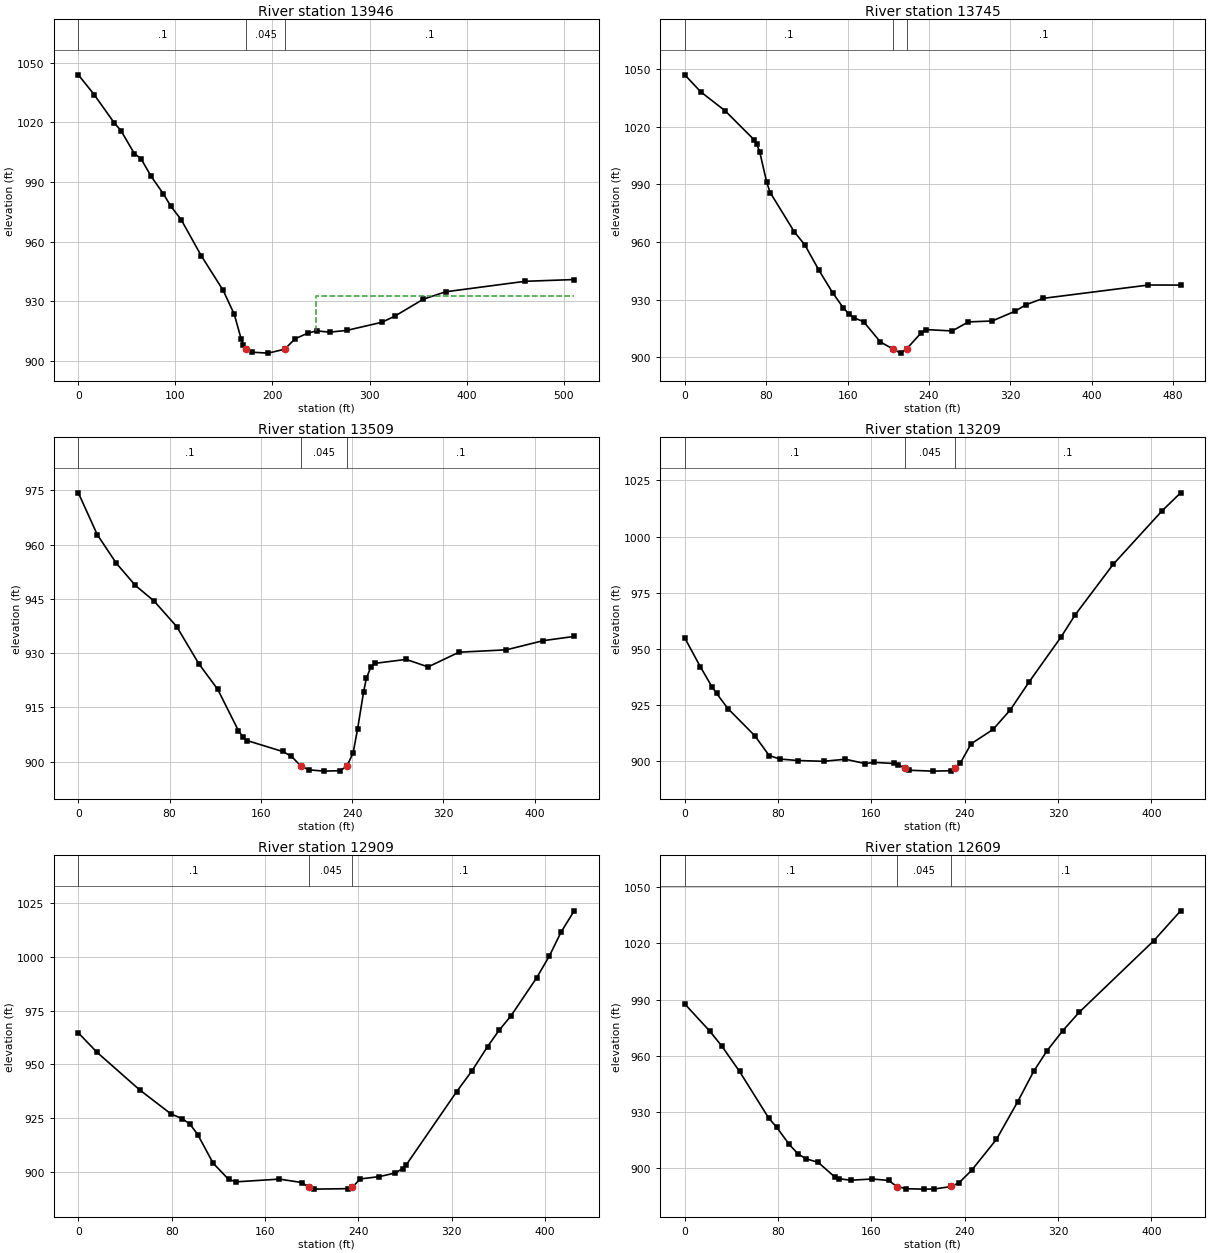
Type RM Length L Ch R = 1 ,13946   ,214.3,200.7,181
XS GIS Cut Line= 4
1652975.73705699454352.0456942331653129.77640196454400.979925682
1653205.08541129454470.3455592531653451.80735427454477.688422187
#Sta/Elev= 30
       0 1043.87    16.4 1033.87      37  1019.7    43.9 1015.83    57.7 1004.28
    64.5 1001.78    74.9  992.91    87.6  984.03    95.5  977.68   105.9  971.09
   126.5  953.04   149.2  935.51   160.7  923.44   167.8  910.95   170.1  907.86
  173.11905.9568   179.4  904.42   195.6  903.97  212.66905.9528   223.2  911.15
   236.6  914.06   245.5  915.15   258.9  914.51   276.6   915.4   312.7  919.48
   325.9  922.52   355.4  931.08   378.4  934.81   460.4  940.08   510.8  940.96
#Mann= 3 ,-1,0
       0      .1       0  173.11    .045       0  212.66      .1       0
#XS Ineff= 2 , 0
                          245.22          932.49
Permanent Ineff=
       F       F
Bank Sta=173.11,212.66
XS Rating Curve= 0 ,0
Exp/Cntr(USF)=0,0
Exp/Cntr=0.3,0.1

Type RM Length L Ch R = 1 ,13745   ,240.9,235.7,227.9
XS GIS Cut Line= 4
1652946.68803099454643.1035953741653110.15784214454596.962897602
1653172.39303742 454590.449912051653415.17335251454512.778936341
#Sta/Elev= 30
       0 1046.87    15.7    1038    39.6 1028.19    67.9 1013.22    70.6 1011.08
    73.7 1006.66    80.5  990.98    83.9  985.68   107.7  965.19     118  958.45
   131.6  945.46   145.2  933.68   155.7  925.78     161  922.74   166.3  920.54
   175.7  918.55   192.2  908.02  204.42904.3694     212  902.19  217.94904.3595
   231.8  912.43     237  914.44   262.8  913.72   278.7  918.42   302.1   918.9
   324.8  924.03   335.1  927.31   352.3  930.67   455.7   937.6   487.3  937.57
#Mann= 3 ,-1,0
       0      .1       0  204.42    .045       0  217.94      .1       0
Bank Sta=204.42,217.94
XS Rating Curve= 0 ,0
Exp/Cntr(USF)=0,0
Exp/Cntr=0.3,0.1

Type RM Length L Ch R = 1 ,13509   ,297.3,300,301.3
XS GIS Cut Line= 6
1653221.97951317454909.9835225051653268.25763585454835.723500416
1653307.92520742454772.0720529261653360.81453735454687.203128174
1653400.48145276454623.5516806691653479.06922209454566.679747179
#Sta/Elev= 30
       0  974.28    16.6  962.71    33.3  954.82      50  948.68    66.3   944.4
    86.2  937.32   105.5  927.09   122.2  919.95   140.3  908.56   144.2  906.83
     148  905.81     179  902.81   186.7  901.49  195.24898.7067   202.2  897.73
   215.2  897.38   229.2   897.5   235.3898.7075   240.8  902.43   244.7  908.99
     250  919.31   252.4     923   256.3  926.13   259.6  927.15   287.2  928.25
   306.5  926.18   333.6  930.24   375.1   930.9   407.5  933.44   434.5   934.6
#Mann= 3 ,-1,0
       0      .1       0  195.24    .045       0   235.3      .1       0
Bank Sta=195.24,235.3
XS Rating Curve= 0 ,0
Exp/Cntr(USF)=0,0
Exp/Cntr=0.3,0.1

Type RM Length L Ch R = 1 ,13209   ,284.2,300,315.6
XS GIS Cut Line= 6
1653470.17619526455042.4937561751653522.32340068454972.227492511
1653567.48735234454912.3506437541653627.70639201454832.515501589
1653672.87034367454772.6386528461653725.56183934454702.783149511
#Sta/Elev= 30
       0  954.85    13.4  941.98    23.2  933.21    27.3  930.16    36.9  923.46
      60  911.34    72.3  902.53    81.4  900.96    96.8  900.31   118.9  899.95
   137.7  900.88   154.4  898.96   162.5  899.46     179  898.98   183.1  898.51
  188.45896.7813   191.8  895.98   212.6  895.58   228.3  895.75  231.99896.7819
   236.1  899.12   245.4  907.73   264.2  914.14     279  922.84   295.3  935.44
   322.6  955.37   334.4  965.02   367.2  987.66   409.1 1011.49     425  1019.5
#Mann= 3 ,-1,0
       0      .1       0  188.45    .045       0  231.99      .1       0
Bank Sta=188.45,231.99
XS Rating Curve= 0 ,0
Exp/Cntr(USF)=0,0
Exp/Cntr=0.3,0.1

Type RM Length L Ch R = 1 ,12909   ,289,300,310.4
XS GIS Cut Line= 6
1653536.35257208455136.8449454161653622.99741192455124.641885832
1653697.26432376455114.1816049221653796.28709158455100.234782428
1653870.55400342455089.7745015031653957.19884326455077.569801509
#Sta/Elev= 30
       0  964.66    16.1  955.57    52.6   938.1    79.3  926.96      89  924.71
    95.7  922.18   102.3  917.34   115.5  904.03   128.8  896.43   135.4  895.31
   172.3  896.57   191.7  894.98  197.37892.7458   201.7  891.91   231.5  892.13
  234.98892.7439   241.4  896.63     258  897.74   271.3  899.37   277.9  901.42
   281.2  903.31   324.3   937.3   337.5  947.06   350.8  958.31   360.7   965.9
   370.7  972.47     393  990.43   403.8  1000.5   413.7  1011.5     425 1021.48
#Mann= 3 ,-1,0
       0      .1       0  197.37    .045       0  234.98      .1       0
Bank Sta=197.37,234.98
XS Rating Curve= 0 ,0
Exp/Cntr(USF)=0,0
Exp/Cntr=0.3,0.1

Type RM Length L Ch R = 1 ,12609   ,301,300,299.3
XS GIS Cut Line= 6
1653499.26143892455314.2415722611653580.07131667455347.798263669
1653649.33692618 455376.561001421653741.69041601455414.911318421
1653810.95602551455443.6740561721653891.76590326455477.230419502
#Sta/Elev= 30
       0  987.74    21.3  973.31    31.8  965.22    46.9  951.77    71.9  926.91
    78.8  921.95    89.5  912.83      97  907.81   103.7  905.22   114.3  903.29
   128.5  895.49   132.1  894.54   142.2  893.74   160.5  894.38   174.7  893.63
  181.68890.3906   189.9  889.19     205  888.99   213.8  889.06  228.53890.3931
   235.1   892.4   245.8  898.99   267.1  915.52   285.3  935.56     299  951.75
   310.4  962.71   323.9  973.43     338  983.27   402.1 1021.54     425 1037.41
#Mann= 3 ,-1,0
       0      .1       0  181.68    .045       0  228.53      .1       0
Bank Sta=181.68,228.53
XS Rating Curve= 0 ,0
Exp/Cntr(USF)=0,0
Exp/Cntr=0.3,0.1

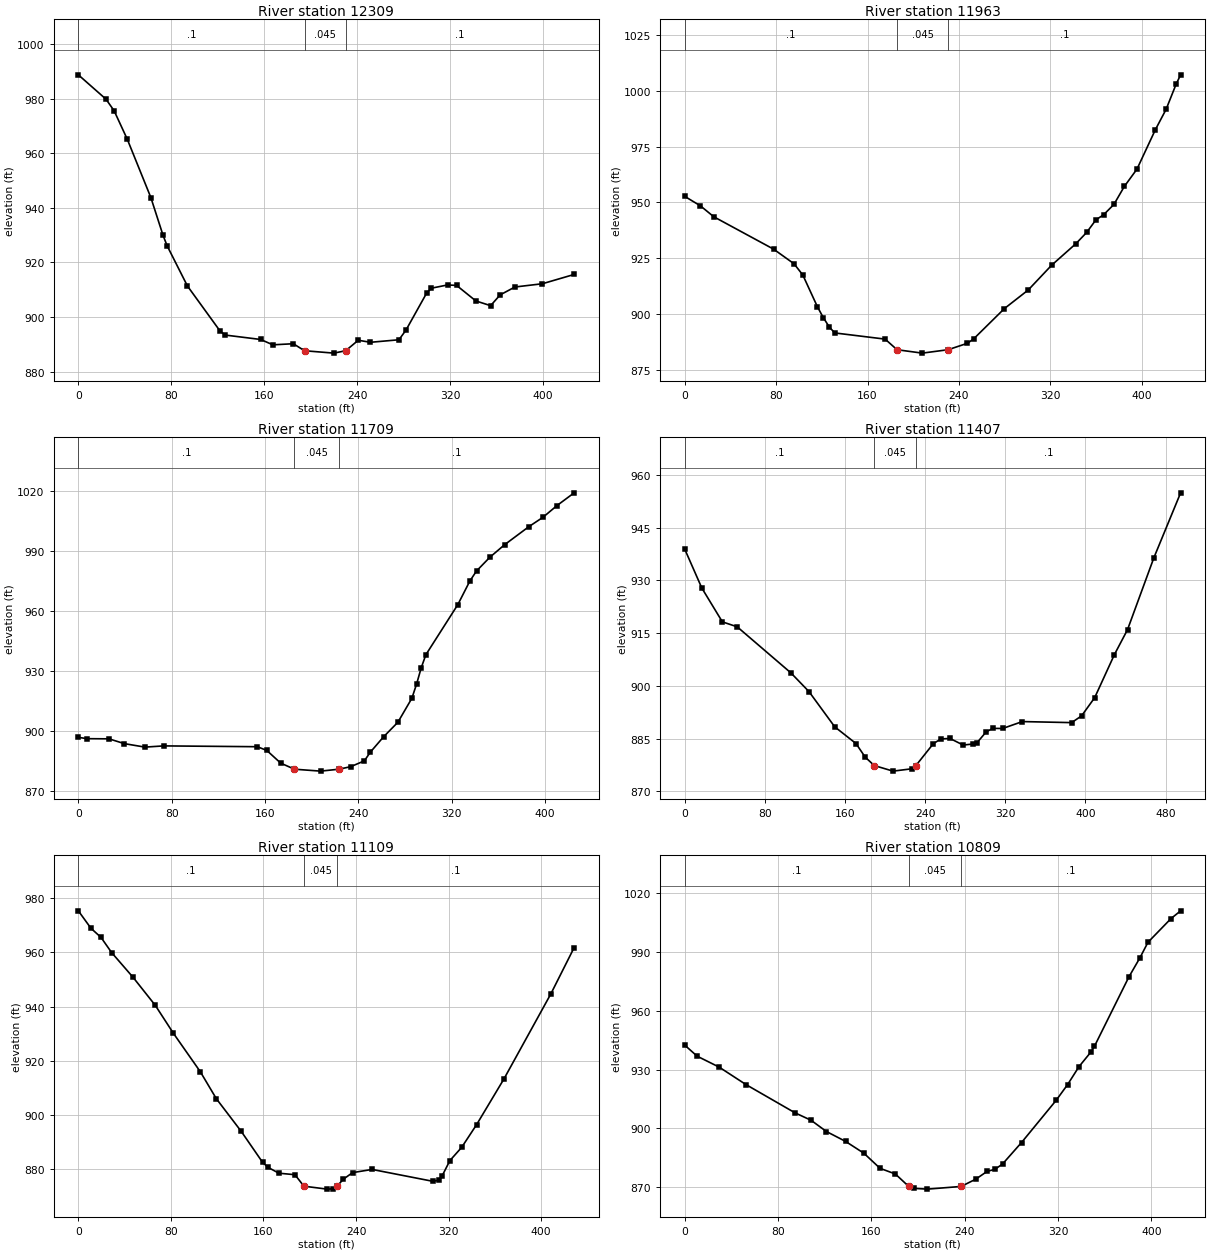
Type RM Length L Ch R = 1 ,12309   ,330.4,345.7,350.5
XS GIS Cut Line= 6
1653382.37322126455598.8650187551653464.35894968455629.436151832
1653534.63243118455655.6401676681653628.33007842455690.579402253
1653698.85421559  455716.33624051653785.79334617455735.971043751
#Sta/Elev= 30
       0  988.68    23.8  979.76    30.8  975.52    42.2  965.02    62.4  943.76
    72.9  929.91    76.4  926.09    93.9  911.35   121.9  894.91   126.3   893.4
   156.9  891.78   167.4  889.82     185  890.22  194.68887.6561   219.9  886.78
  230.06887.6584   240.9  891.49   251.4  890.75   275.9  891.67     282  895.23
   299.9  908.88   303.8  910.55   317.7  911.74   325.5  911.58   342.1  905.89
   354.8  904.16     363   908.1   375.7  910.99   399.3  912.18   426.7  915.59
#Mann= 3 ,-1,0
       0      .1       0  194.68    .045       0  230.06      .1       0
Bank Sta=194.68,230.06
XS Rating Curve= 0 ,0
Exp/Cntr(USF)=0,0
Exp/Cntr=0.3,0.1

Type RM Length L Ch R = 1 ,11963   ,260,254.3,251.7
XS GIS Cut Line= 3
1653338.85395133455767.6724239291653383.34590094455890.018866497
1653593.74878275456109.257370666
#Sta/Elev= 30
       0  952.72    13.7  948.49    25.4   943.6    77.8  929.09    95.6  922.57
   103.3  917.56   116.1  903.31   121.2  898.49   126.6  894.18   131.3  891.59
   175.4  888.82  185.81884.0776   207.9  882.55  230.53884.0787   247.4  886.95
   252.9  888.93   279.8  902.49   300.7  910.83   321.1  921.88   342.5   931.6
   351.8  936.58     360  942.26   366.6  944.47   375.7  949.13   384.8  957.17
   395.9  964.96     412   982.6   421.4  991.73   430.2 1003.04   434.1 1007.16
#Mann= 3 ,-1,0
       0      .1       0  185.81    .045       0  230.53      .1       0
Bank Sta=185.81,230.53
XS Rating Curve= 0 ,0
Exp/Cntr(USF)=0,0
Exp/Cntr=0.3,0.1

Type RM Length L Ch R = 1 ,11709   ,300.7,302.4,302.8
XS GIS Cut Line= 6
1653111.97678043456027.9527432621653183.49402584456078.366356343
1653244.79442817456121.5782121721653326.52786051456179.194238678
1653387.82859093456222.4057664281653459.34550826456272.819707587
#Sta/Elev= 30
       0  896.85     7.5  896.17    26.3  896.09    39.5  893.69    57.1  891.96
    73.2  892.57   153.4  892.16   161.5  890.32   173.5  883.95  185.26880.9328
   207.6  879.97  223.46880.9327   233.5   882.2   245.2  885.11   250.2  889.38
   261.7  897.14   273.9  904.37   285.9  916.36     290  923.56   293.9  931.56
   297.9  938.09   325.3  963.13   335.6  974.89   341.3   979.9   352.7  986.74
   365.3  992.98   386.2 1002.05   398.3 1006.72   410.3 1012.58     425 1018.93
#Mann= 3 ,-1,0
       0      .1       0  185.26    .045       0  223.46      .1       0
Bank Sta=185.26,223.46
XS Rating Curve= 0 ,0
Exp/Cntr(USF)=0,0
Exp/Cntr=0.3,0.1

Type RM Length L Ch R = 1 ,11407   ,327.3,297.6,269.6
XS GIS Cut Line= 5
1652948.43281618456230.2876404231653010.30473967456292.159563929
1653055.74102374456349.9405608021653132.16014412456409.698324368
 1653369.0418831456404.544509754
#Sta/Elev= 30
       0  938.87      17  927.84    37.5  918.22    52.3  916.81   105.9  903.71
     124  898.37   149.7  888.35   170.9   883.6   180.1  879.73  189.15877.3367
   207.9  875.75   226.8  876.42  230.74877.3389   248.2  883.59   255.8  884.92
   264.8  885.04   277.9  883.17   287.8  883.47   291.7  883.82   300.9  886.93
   307.5  887.91   317.3  887.88     337  889.85   386.2  889.55   396.1  891.47
   409.2  896.65   428.9  908.91     442  916.01   468.3  936.46     495  954.93
#Mann= 3 ,-1,0
       0      .1       0  189.15    .045       0  230.74      .1       0
Bank Sta=189.15,230.74
XS Rating Curve= 0 ,0
Exp/Cntr(USF)=0,0
Exp/Cntr=0.3,0.1

Type RM Length L Ch R = 1 ,11109   ,282.3,300,311.1
XS GIS Cut Line= 6
1653091.90989143456749.8354858461653153.78181492 456687.96356234
1653206.81484534456634.9308600131653277.52566193456564.220043421
1653330.36807592456510.9963965861653404.71405584456458.604112923
#Sta/Elev= 30
       0  975.24    10.9  968.82    19.6  965.45    28.8  959.85    47.4   950.7
    66.5  940.43    82.2  930.11   105.4  915.99   119.3  906.02   140.8     894
   159.3  882.57     164  880.74   173.3  878.61   187.2  878.05  194.93873.8242
     215  872.74   219.7  872.84  223.63873.8243   228.9  876.36     237  878.82
   253.9  879.99   306.5  875.61   311.9  876.09   314.2  877.45   321.1  883.25
   331.3  888.13   344.2   896.5     368  913.46   408.4  944.69   428.5  961.71
#Mann= 3 ,-1,0
       0      .1       0  194.93    .045       0  223.63      .1       0
Bank Sta=194.93,223.63
XS Rating Curve= 0 ,0
Exp/Cntr(USF)=0,0
Exp/Cntr=0.3,0.1

Type RM Length L Ch R = 1 ,10809   ,298.5,300,300.7
XS GIS Cut Line= 6
1653145.58793367456850.8431578431653233.03198451 456847.71980451
1653307.98426242456845.0429725951653407.92041425456841.473425925
1653482.94585475 456840.843177841653570.51588959456841.236877844
#Sta/Elev= 30
       0  942.48    10.6  936.87    29.5  931.28    52.5  922.37    94.6  907.94
   108.3  904.16   121.4  898.44   137.8  893.41   153.6  887.33   167.4  879.65
   180.5  876.77  192.02870.4044   196.9  869.41     208  869.04  236.88870.4053
   249.4   874.1   259.3  878.13   265.8  879.12   272.4  881.84   288.7  892.82
   318.3  914.29   328.2  922.38     338  931.57   347.9  938.79   351.2   941.9
   380.7  977.26   390.2  987.06   397.1  994.99   416.8 1007.06   425.1 1011.04
#Mann= 3 ,-1,0
       0      .1       0  192.02    .045       0  236.88      .1       0
Bank Sta=192.02,236.88
XS Rating Curve= 0 ,0
Exp/Cntr(USF)=0,0
Exp/Cntr=0.3,0.1

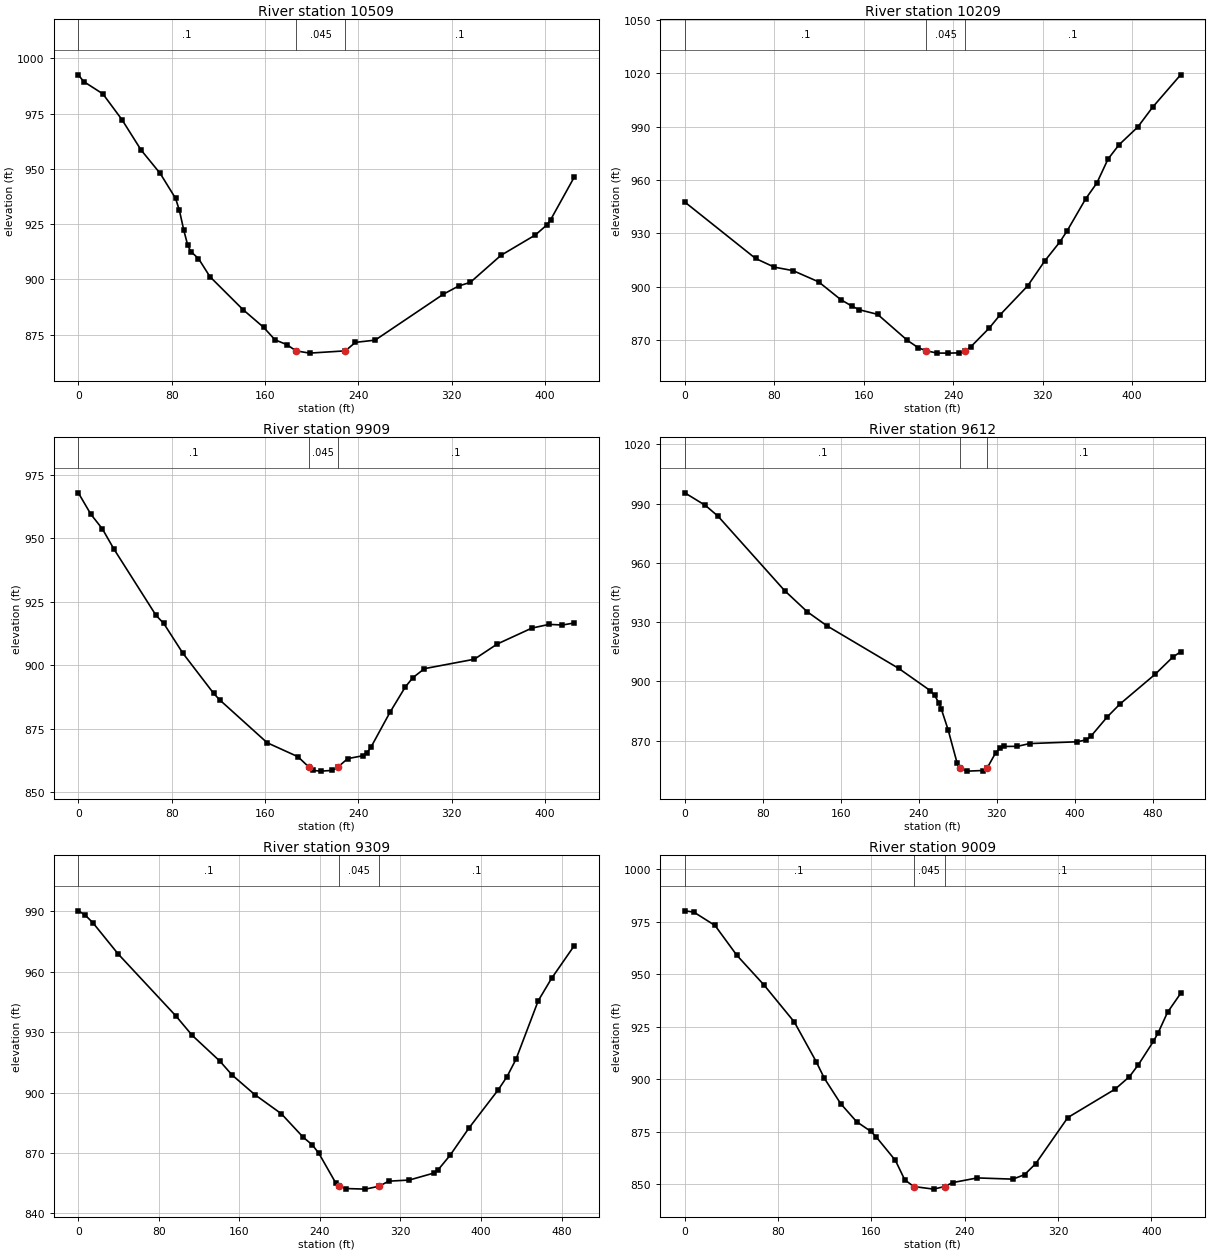
Type RM Length L Ch R = 1 ,10509   ,305.6,300.5,296.4
XS GIS Cut Line= 6
 1653157.3549705457139.2559668421653244.84626535457140.471187502
1653319.83889751457141.5131801661653419.82951118457142.901956916
1653494.82214335457143.9432934221653582.31376626457145.158514082
#Sta/Elev= 30
       0  992.54     4.6  989.49      21  983.94    37.4  972.26    53.8  958.52
    70.2  947.91    83.3   936.7    86.6  931.31    90.4  922.24    93.8  915.41
    96.4  912.61     103  909.43   112.8  901.24   141.1  886.36   158.8  878.34
   168.6  872.66   178.5  870.56  186.64 867.692   198.2  866.66   228.9867.6904
   237.5  871.53   254.4  872.53     313  893.35   326.1  897.05     336  898.67
   362.2  910.87   391.7  920.09   401.6  924.64   404.9  927.05     425   946.2
#Mann= 3 ,-1,0
       0      .1       0  186.64    .045       0   228.9      .1       0
Bank Sta=186.64,228.9
XS Rating Curve= 0 ,0
Exp/Cntr(USF)=0,0
Exp/Cntr=0.3,0.1

Type RM Length L Ch R = 1 ,10209   ,297,299.5,302.1
XS GIS Cut Line= 6
1653230.65436459457448.2143384221653326.19255935457432.582479924
1653407.39613709 457424.624162511653508.45892709457407.598277926
 1653582.5273485457395.814836919 1653668.9405615457382.067489088
#Sta/Elev= 30
       0  947.59    63.3  915.83      80  910.97    96.8  908.99   119.7  902.67
   139.4  892.71   149.3  889.06   155.9     887   172.4   884.4     199  869.78
   208.9  865.55   216.1 863.866   225.6  862.61   235.2  862.57   245.5  862.71
  250.87863.8649   255.5  865.97   272.2  876.63   282.1  884.22   306.6   900.4
     322  914.53   335.3  925.04   341.9  931.37   358.5   949.4   368.5   958.3
   378.5  971.81   388.4  979.86   405.1  989.81   418.3 1000.91   443.4 1019.17
#Mann= 3 ,-1,0
       0      .1       0   216.1    .045       0  250.87      .1       0
Bank Sta=216.1,250.87
XS Rating Curve= 0 ,0
Exp/Cntr(USF)=0,0
Exp/Cntr=0.3,0.1

Type RM Length L Ch R = 1 ,9909    ,306.9,296.8,287
XS GIS Cut Line= 6
1653229.98966776457720.339778423 1653317.3192175457714.881784096
1653392.17307043457710.2036438441653491.97831701457703.966779679
1653566.83216992457699.2879832541653654.23291376457694.967125759
#Sta/Elev= 30
       0   967.9    10.7  959.49    20.6  953.71    30.4  945.85    66.6  919.67
    73.2  916.51    89.6  904.79   115.9  889.03   121.1  886.44   161.9  869.54
   188.2  864.06   197.9 859.864   201.4  858.64   207.8  858.38   217.8  858.66
  222.18859.8647   230.9   863.3   244.1  864.45   247.4  865.61   250.7  867.69
   267.1   881.5   280.2  891.46   286.8  895.18   296.7  898.71   339.4  902.41
   359.1  908.41   388.7  914.66   403.4  916.12     415  915.89     425  916.67
#Mann= 3 ,-1,0
       0      .1       0   197.9    .045       0  222.18      .1       0
Bank Sta=197.9,222.18
XS Rating Curve= 0 ,0
Exp/Cntr(USF)=0,0
Exp/Cntr=0.3,0.1

Type RM Length L Ch R = 1 ,9612    ,262.4,303.2,337.6
XS GIS Cut Line= 6
1653290.93442775457934.9515539261653412.10347676457981.943585917
1653525.72037551458004.0327805881653593.68939967457930.507993251
1653643.38647875457874.2515440881653702.71575642 457809.71558392
#Sta/Elev= 30
       0   995.4    21.2  989.01    34.1  983.57   102.3  945.99   125.5   935.3
   145.8  928.14   219.4  906.61   251.8  895.37   256.3  892.92   260.8  889.03
   263.1  886.11   270.1  875.57   279.3  858.82  282.08856.0749   289.8  854.66
   305.5  854.97  309.97856.0745   318.8  863.85   323.3  866.27   327.8  867.14
   341.2   867.2   353.6  868.59   402.6   869.5   411.8  870.48   416.4   872.2
   433.4  882.11   446.3  888.56   482.5  903.66   500.3   912.2   508.6  915.03
#Mann= 3 ,-1,0
       0      .1       0  282.08    .045       0  309.97      .1       0
Bank Sta=282.08,309.97
XS Rating Curve= 0 ,0
Exp/Cntr(USF)=0,0
Exp/Cntr=0.3,0.1

Type RM Length L Ch R = 1 ,9309    ,309.4,300.2,293.2
XS GIS Cut Line= 6
1653274.54141593457957.0056436661653379.31679693458026.052093506
1653460.14701584458092.249139592  1653471.057099 458191.65215601
1653479.23982543458266.2045003321653488.78639425 458353.18234475
#Sta/Elev= 30
       0  990.28     6.6  988.25    14.4  984.39    39.4  968.93    96.9  938.05
     113  928.45   140.6  915.59   152.6  908.76   175.3  898.94   201.6  889.47
   223.4  877.75   232.5  873.94     239   869.7   255.5  855.22  258.81853.4175
   265.4  852.29   285.2  851.99  298.63853.4174   308.3  855.94   328.7   856.5
   353.3  859.99   357.4  861.61   369.3  868.83     388  882.35   417.2  901.41
   425.8  907.88   434.7  916.48   456.8  945.58     470  956.66   492.5  972.89
#Mann= 3 ,-1,0
       0      .1       0  258.81    .045       0  298.63      .1       0
Bank Sta=258.81,298.63
XS Rating Curve= 0 ,0
Exp/Cntr(USF)=0,0
Exp/Cntr=0.3,0.1

Type RM Length L Ch R = 1 ,9009    ,296.1,299.8,301.8
XS GIS Cut Line= 6
1653056.37387326458055.7262467591653108.97514601 458125.66639559
1653154.16370392458185.5363545861653214.52742834458265.263229251
1653259.29833618458325.4340406661653311.52526584458395.630750671
#Sta/Elev= 30
       0  980.15     7.7  979.55    25.9  973.18    44.6  959.01      68   944.8
    93.9  927.24   112.6  908.43   119.6   900.5   133.6  888.42   147.3  879.81
   159.4  875.25   163.8  872.76   180.5  861.43   188.5  852.22  196.17848.9986
   213.2  847.75  222.79848.9977   229.6  850.86   250.7  853.08   281.2   852.5
   291.2  854.63   300.8  859.89   328.3   881.8   368.9  895.33   381.1  901.24
   388.8  906.95   401.6  917.99   405.7  922.07   413.8  931.88     425  940.85
#Mann= 3 ,-1,0
       0      .1       0  196.17    .045       0  222.79      .1       0
Bank Sta=196.17,222.79
XS Rating Curve= 0 ,0
Exp/Cntr(USF)=0,0
Exp/Cntr=0.3,0.1

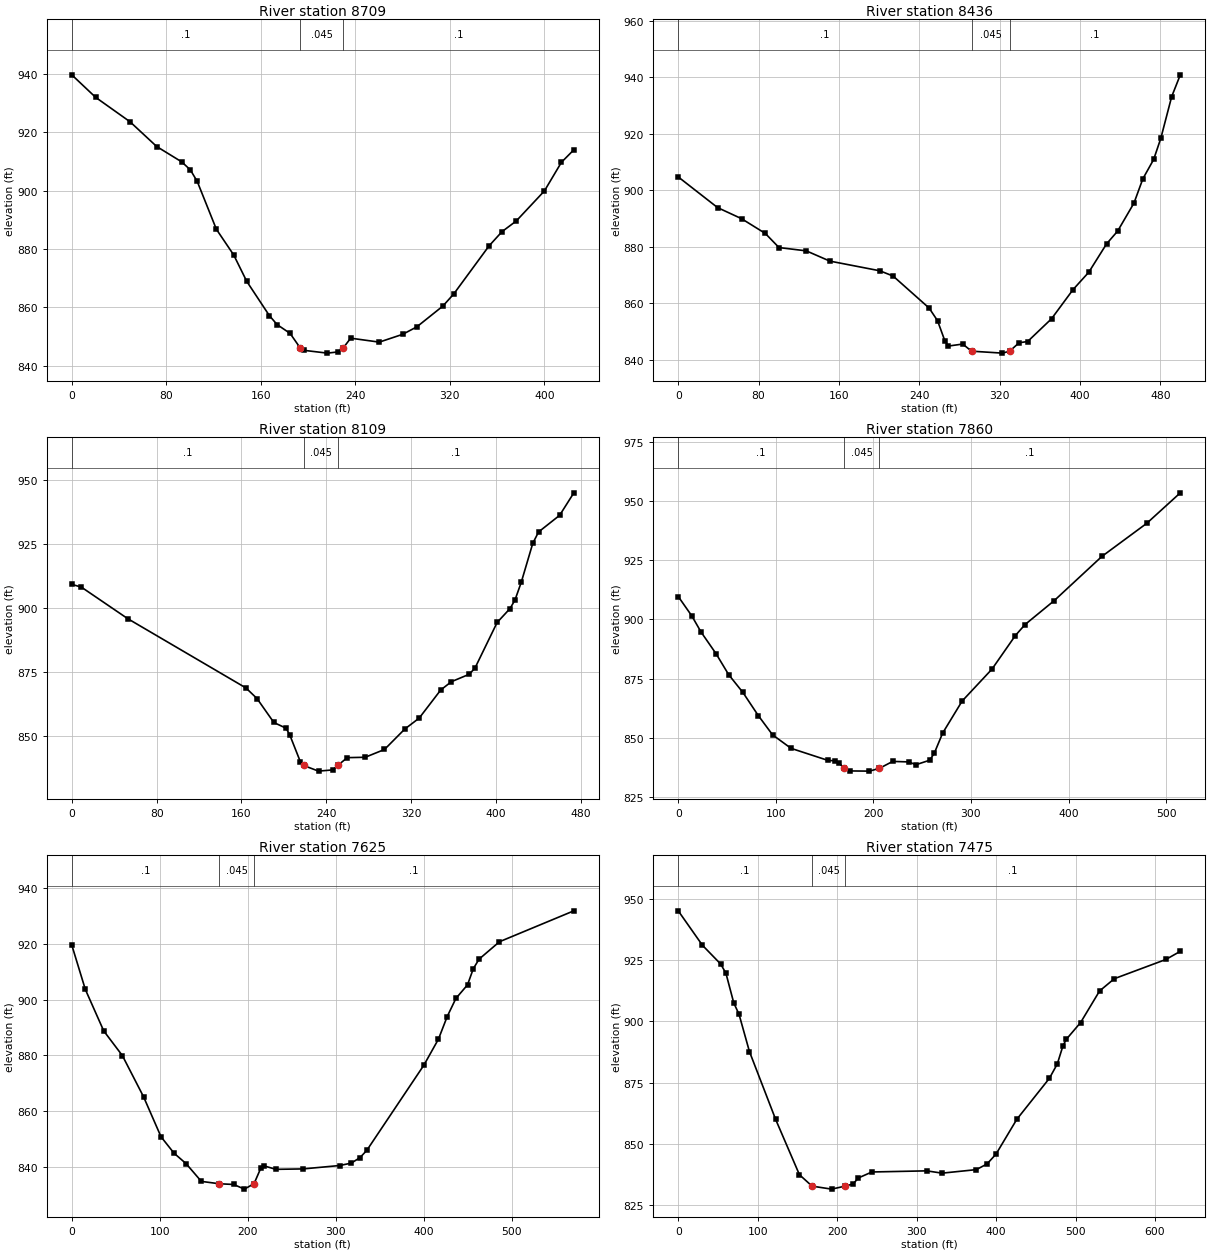
Type RM Length L Ch R = 1 ,8709    ,272.9,273.5,275
XS GIS Cut Line= 6
1652834.81165235458184.7437052581652872.76958168458263.592628926
1652906.31085317458330.674515754 1652951.0325485458420.117250249
1652984.57349193458487.1991370921653022.10064784458566.263283417
#Sta/Elev= 30
       0  939.65    20.2  931.94    49.3  923.58    71.9  915.09    93.1  909.83
   100.4  907.08   106.2  903.14   122.4  886.76   137.1  877.94   148.1  868.92
   167.3  857.16   173.8  854.11   184.8  851.09  193.43846.0723   196.7  845.28
   216.3  844.33   225.1  844.73   229.7  846.07   236.1  849.45   260.3   848.1
   280.1  850.77   292.1  853.33   314.1  860.44   323.3  864.57   353.3   881.1
   364.2  885.94   376.2  889.57   400.1  899.89   414.5   909.7     425  913.97
#Mann= 3 ,-1,0
       0      .1       0  193.43    .045       0   229.7      .1       0
Bank Sta=193.43,229.7
XS Rating Curve= 0 ,0
Exp/Cntr(USF)=0,0
Exp/Cntr=0.3,0.1

Type RM Length L Ch R = 1 ,8436    ,297.9,326.5,360.9
XS GIS Cut Line= 4
1652741.99786159458247.0214678351652706.79058293458380.404403165
1652691.38816469458484.6149327211652794.85347751458719.310910005
#Sta/Elev= 30
       0  904.69    39.2  893.83      63  889.92    86.7  884.69   100.3   879.7
   127.5  878.53   150.9  874.91   200.7  871.48   213.9  869.62   249.7  858.31
   258.1  853.85   265.3  846.81   268.9  844.85   283.2  845.56     292  843.04
   322.7  842.35   329.9  843.03   339.3  846.02   347.8  846.45   371.6  854.51
   393.1  864.86   408.7  870.98   426.4  881.01   437.4  885.52   453.7  895.46
   462.5  904.02   473.3  910.89   480.4  918.37   491.2  933.09   499.8  940.81
#Mann= 3 ,-1,0
       0      .1       0     292    .045       0   329.9      .1       0
Bank Sta=292,329.9
XS Rating Curve= 0 ,0
Exp/Cntr(USF)=0,0
Exp/Cntr=0.3,0.1

Type RM Length L Ch R = 1 ,8109    ,254,249,243.2
XS GIS Cut Line= 6
1652717.47658518458202.0110591651652657.74835818458290.383913919
1652586.68550818458317.8097120821652489.92389068458343.052443758
1652417.35284159458361.9848205891652347.99799342458454.322234333
#Sta/Elev= 30
       0  909.21       9  908.15    52.6  895.87   164.2  868.79   174.6  864.67
   190.5  855.31     202  853.08   205.4  850.57   215.6  839.87  218.49838.5493
   232.6  836.33   246.1  836.81  250.71 838.551   259.7  841.59   276.6  841.74
   294.8  844.78   313.9  852.74   327.5  857.02   347.8  867.99   357.8  871.22
   374.5   874.1     380  876.47     401  894.36   413.1  899.76   417.8   903.1
   423.7     910   434.6  925.26   440.1  929.69   459.9  936.16   473.3  944.94
#Mann= 3 ,-1,0
       0      .1       0  218.49    .045       0  250.71      .1       0
Bank Sta=218.49,250.71
XS Rating Curve= 0 ,0
Exp/Cntr(USF)=0,0
Exp/Cntr=0.3,0.1

Type RM Length L Ch R = 1 ,7860    ,231.2,235.5,233.8
XS GIS Cut Line= 3
1652580.71736122458009.3392173911652297.77138785458196.878523499
1652288.20743059458371.769249842
#Sta/Elev= 30
       0  909.69    13.9  901.51    23.3  894.75    38.8  885.53    51.7  876.71
    66.3  869.19      82  859.47    96.7  851.31   115.6  845.62   153.5  840.52
   160.8  840.36   164.7  839.57  169.86837.1712   176.5  836.08     196     836
   206.2 837.174   219.8   840.1   236.4  839.89   243.5  838.69   257.7   840.6
   262.4  843.52     271  852.04     291  865.58   321.6  879.06   345.5  893.19
   355.4  897.83   385.5     908   434.2   926.6   480.2  940.57   514.6  953.44
#Mann= 3 ,-1,0
       0      .1       0  169.86    .045       0   206.2      .1       0
Bank Sta=169.86,206.2
XS Rating Curve= 0 ,0
Exp/Cntr(USF)=0,0
Exp/Cntr=0.3,0.1

Type RM Length L Ch R = 1 ,7625    ,166.7,149.1,137.8
XS GIS Cut Line= 4
1652409.06318179457825.2899987041652325.49897196457919.299734763
 1652202.0518438457996.2167915391652236.23720236458293.439492412
#Sta/Elev= 30
       0  919.58    15.4  903.65    36.3  888.77    57.5   879.9    81.6   865.1
   101.4  850.77   116.2  844.88   129.9  841.13   147.2  834.77   167.5  833.92
     184  833.66   196.1  831.99  207.08833.9373   214.9  839.63   218.8  840.31
   231.8  839.09   262.7  839.24   304.3  840.46   317.5  841.32   327.4  843.28
   335.2  845.91   400.1  876.51   416.6  885.83   426.5   893.9   436.4  900.41
   449.6  905.29   456.2  911.11   462.8  914.53   485.9  920.76   570.4  931.85
#Mann= 3 ,-1,0
       0      .1       0   167.5    .045       0  207.08      .1       0
Bank Sta=167.5,207.08
XS Rating Curve= 0 ,0
Exp/Cntr(USF)=0,0
Exp/Cntr=0.3,0.1

Type RM Length L Ch R = 1 ,7475    ,299.1,274.7,248.4
XS GIS Cut Line= 5
1652180.10255514457680.5764943311652168.00010882457819.517971426
1652143.35719604 457921.241072421652151.41544872458056.290328156
1652219.88407642458299.155878007
#Sta/Elev= 30
       0  945.11    30.4  931.07    53.4  923.39      60  919.64    69.9  907.49
    76.5  902.87    89.6  887.66   122.6  859.94   152.5  837.39  168.37832.7236
     193   831.5   209.8  832.71     220  833.61   226.8  836.08   243.7   838.5
   312.7  838.96     332  838.02   375.1  839.46   388.6  841.78   399.9   845.8
   426.1  860.02     467  876.71     477   882.6   484.1  889.97   488.3  892.65
   506.3  899.49   530.2  912.39   548.8  917.41   613.6  925.25   631.8  928.58
#Mann= 3 ,-1,0
       0      .1       0  168.37    .045       0   209.8      .1       0
Bank Sta=168.37,209.8
XS Rating Curve= 0 ,0
Exp/Cntr(USF)=0,0
Exp/Cntr=0.3,0.1

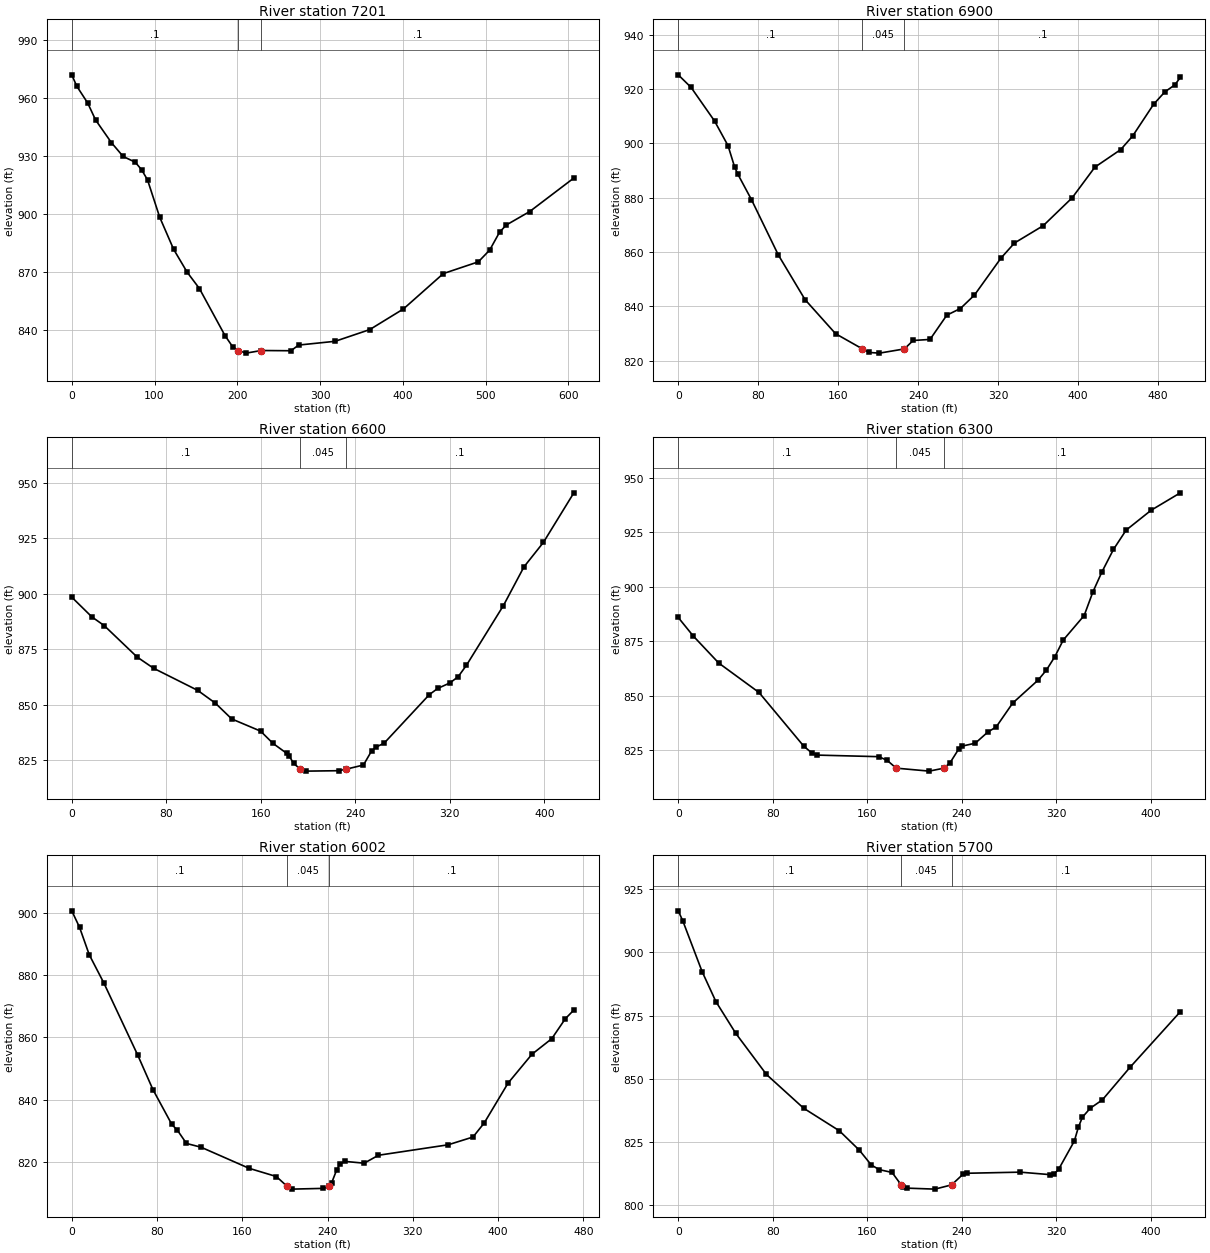
Type RM Length L Ch R = 1 ,7201    ,309.8,300.8,288.2
XS GIS Cut Line= 6
1651771.47454017457921.8899002521651849.33363642457961.817313835
1651916.07005151457996.0409986671652005.75786425458040.295831427
1652084.26492509458110.6998900921652181.45403518458328.680097178
#Sta/Elev= 30
       0  971.82       6  965.98    19.2  957.29    28.8   948.5    47.9   936.8
    62.1  929.66    76.7  926.71    84.4  922.79    91.5   917.6   106.2  898.35
     123  881.78   139.4  869.91   154.2  861.48   185.2  837.12   194.5  831.34
  201.22 829.475   210.7  828.12  228.94829.4709   264.8  829.35   274.1  832.28
   318.2  834.23     360  840.27   400.7  850.93   448.9  869.19   491.2  875.26
   504.9  881.32   516.8  890.52   524.9  894.25   553.3  901.24   606.6  918.53
#Mann= 3 ,-1,0
       0      .1       0  201.22    .045       0  228.94      .1       0
Bank Sta=201.22,228.94
XS Rating Curve= 0 ,0
Exp/Cntr(USF)=0,0
Exp/Cntr=0.3,0.1

Type RM Length L Ch R = 1 ,6900    ,281.4,300,306.5
XS GIS Cut Line= 6
1651758.41879201458356.1741366681651843.78509109458336.945172504
1651916.76624434458319.6601020841652014.07444867458296.614216417
1652086.76820092458278.1165499991652182.70600118458412.388263091
#Sta/Elev= 30
       0  925.18    12.8  920.58    36.3  908.22    49.8  899.15    56.5   891.2
    59.8  888.53    73.3  879.26   100.2   858.9   126.9   842.5   157.5  829.95
  184.37824.3592   191.3  823.05   201.4  822.81  226.36824.3593   235.1  827.46
     252  827.85   268.8  836.77   282.4  839.22   296.5  844.18     323  857.76
   336.5  863.31   365.3  869.69   394.3  879.96     417  891.22   442.9  897.69
   454.8  902.68   475.8  914.35     487   918.9     497  921.48   502.5   924.2
#Mann= 3 ,-1,0
       0      .1       0  184.37    .045       0  226.36      .1       0
Bank Sta=184.37,226.36
XS Rating Curve= 0 ,0
Exp/Cntr(USF)=0,0
Exp/Cntr=0.3,0.1

Type RM Length L Ch R = 1 ,6600    ,279,300,312.5
XS GIS Cut Line= 6
1651715.53633185458502.5147232561651797.91608834458532.007118344
1651868.52749567458557.2865953451651962.67625751458590.991252333
1652033.28733675458616.2704012541652115.66774942458645.761812091
#Sta/Elev= 30
       0   898.4      17  889.52    27.4  885.62    55.3  871.44    69.2  866.39
   106.6  856.41   121.5  850.67   135.4  843.54   159.8  838.06   170.3  832.54
   181.9  828.06   184.2  826.76   187.7  823.55   193.5 820.926   198.2  820.03
     226  820.22  232.37820.9252   246.9  822.78   253.9  829.22   257.4  830.82
   264.4  832.62   302.7  854.51   309.7  857.26   320.1  859.77   327.1  862.58
   334.1  867.73   365.4  894.64   382.8  912.07   399.2  923.05     425  945.41
#Mann= 3 ,-1,0
       0      .1       0   193.5    .045       0  232.37      .1       0
Bank Sta=193.5,232.37
XS Rating Curve= 0 ,0
Exp/Cntr(USF)=0,0
Exp/Cntr=0.3,0.1

Type RM Length L Ch R = 1 ,6300    ,302.1,297.6,285.3
XS GIS Cut Line= 6
1651650.86913835   458601.4269271651686.89662534458681.222371086
1651715.39000668458750.5992008451651753.38205667458843.101312429
  1651781.875438458912.4778140931651815.11848176458993.416956678
#Sta/Elev= 30
       0  885.88    12.7  877.38    34.3  864.94    68.4  851.42   106.1  826.87
   113.1  823.62   117.2  822.66   169.9  821.93     177  820.19  184.54816.6592
   212.5  815.29  225.07816.6613   230.2  819.18   237.3  825.28   240.4  826.79
   251.5  828.12   262.1  833.23   269.2  835.59   283.2  846.56   304.7  857.12
   311.8  861.78   318.9  867.89     326  875.53   343.7  886.78   351.1  897.64
   358.6  906.66   368.5  917.15   379.2     926   400.4  935.15   425.1  943.15
#Mann= 3 ,-1,0
       0      .1       0  184.54    .045       0  225.07      .1       0
Bank Sta=184.54,225.07
XS Rating Curve= 0 ,0
Exp/Cntr(USF)=0,0
Exp/Cntr=0.3,0.1

Type RM Length L Ch R = 1 ,6002    ,311.4,302.4,270.8
XS GIS Cut Line= 6
1651314.44330201458765.2740402521651375.22008334458828.222077087
1651427.31479542458882.1773497611651502.98524776458953.493152007
1651583.30332859 459001.549158261651680.74243817459054.500495926
#Sta/Elev= 30
       0  900.68     7.3  895.38    16.4  886.57    30.1   877.5      62  854.24
    76.1  843.29    93.9  832.05    99.1   830.2   107.6  825.96   121.3  824.75
   166.4  817.97   191.9  815.34  202.13 812.161   206.3  811.29     236  811.53
  241.38 812.162   243.7  813.24   248.4  817.35   251.4  819.24   255.9  820.21
   274.3  819.62   287.7  822.17   353.1  825.53   376.4  828.03   386.9  832.53
   409.3  845.35   431.7  854.61   450.3  859.62     463  866.02     471  868.81
#Mann= 3 ,-1,0
       0      .1       0  202.13    .045       0  241.38      .1       0
Bank Sta=202.13,241.38
XS Rating Curve= 0 ,0
Exp/Cntr(USF)=0,0
Exp/Cntr=0.3,0.1

Type RM Length L Ch R = 1 ,5700    ,298.9,300,303.3
XS GIS Cut Line= 6
1651283.80753651459242.8160641791651368.94680193459222.628768593
  1651441.923362459205.3249974251651539.22566085459182.253521249
1651612.20222092459164.9497500961651697.34148633459144.762126416
#Sta/Elev= 30
       0   916.4     3.9  912.39    20.2  892.39    31.9  880.52    48.7  867.98
    74.7  851.72   106.1  838.41   136.4  829.47   153.3  821.81   163.4  815.98
   170.1  814.13     181  813.01  188.71 808.105   190.4  807.24   193.7  806.81
   217.3  806.42  231.41808.1031   240.9  812.24   244.3  812.69   289.5  813.13
   315.1  812.13   318.5  812.57   321.9  814.18   335.3  825.43   338.7  830.87
   342.1  834.84   348.8   838.4     359  841.68   382.3  854.49     425  876.52
#Mann= 3 ,-1,0
       0      .1       0  188.71    .045       0  231.41      .1       0
Bank Sta=188.71,231.41
XS Rating Curve= 0 ,0
Exp/Cntr(USF)=0,0
Exp/Cntr=0.3,0.1

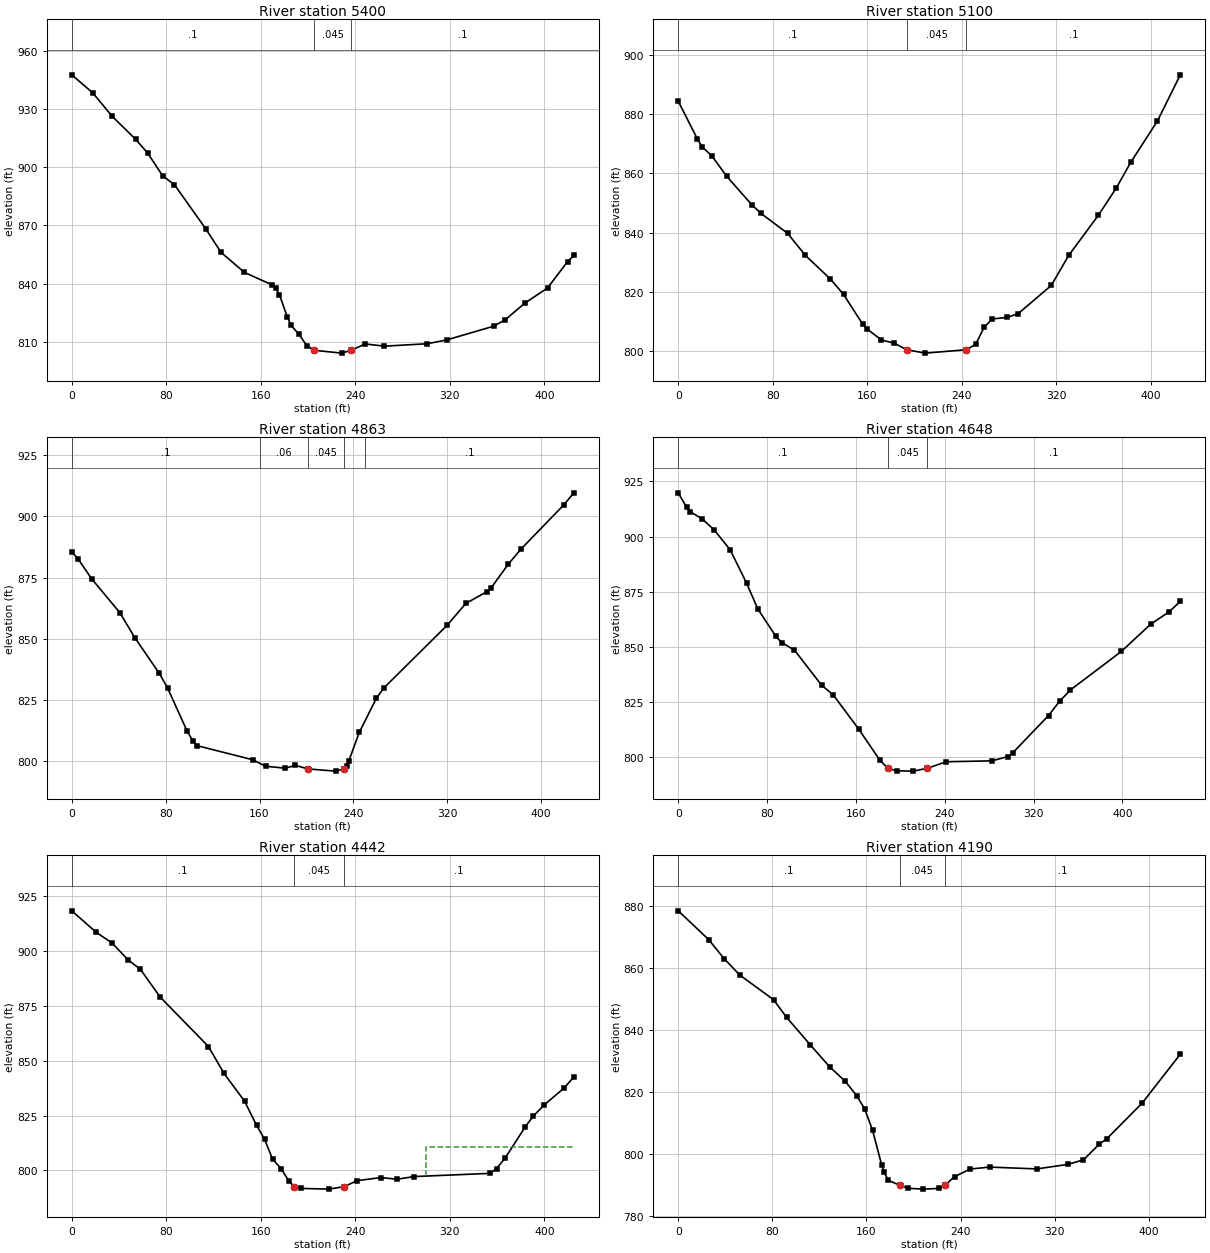
Type RM Length L Ch R = 1 ,5400    ,292,300,314.2
XS GIS Cut Line= 6
1651339.76838259 459504.526498751651426.95784076459497.158075169
1651501.69161518459490.8427990821651601.33577284459482.420571834
1651676.06954725 459476.104639591651763.06313968459466.422244251
#Sta/Elev= 30
       0   947.6    17.8  938.28    34.2  926.21      54   914.4    64.2  907.28
      77   895.5    86.9  890.98   113.3  868.31   126.4  856.04   146.1  845.77
   169.2  839.41   172.5  837.81   175.8  834.28   182.4  822.83   185.7  818.41
   192.3  813.84   198.9  808.05   204.8805.6161   228.5  804.13  236.69805.6172
   248.3  808.86   264.7  807.72   300.9  808.97   317.4  810.94     357  817.99
   366.9  821.31   383.4  829.85   402.7  837.72   419.7  851.29     425  854.49
#Mann= 3 ,-1,0
       0      .1       0   204.8    .045       0  236.69      .1       0
Bank Sta=204.8,236.69
XS Rating Curve= 0 ,0
Exp/Cntr(USF)=0,0
Exp/Cntr=0.3,0.1

Type RM Length L Ch R = 1 ,5100    ,236.4,236.8,238
XS GIS Cut Line= 6
1651329.21886301459685.917540178 1651408.6222475459722.677965343
1651476.68247885459754.1870886681651567.45624742459796.141073003
1651636.18872151459826.1980995091651716.58685467459860.809906915
#Sta/Elev= 30
       0  884.51    16.3  871.61    20.3  869.04    28.7  865.83      41  859.07
    62.3  849.38    70.1  846.45    92.6  839.71   107.7  832.22   128.8  824.23
   139.9  819.05     156  809.02   159.6  807.39     172  803.59     183  802.47
  193.36800.2824   209.1  799.13  243.82 800.282   251.7  802.06   258.9  807.84
   265.7   810.7   278.4  811.24   287.6  812.46   315.8  822.07   330.5  832.22
   355.6  845.82   370.7  855.01   383.1  863.82   405.6  877.77     425  893.43
#Mann= 3 ,-1,0
       0      .1       0  193.36    .045       0  243.82      .1       0
Bank Sta=193.36,243.82
XS Rating Curve= 0 ,0
Exp/Cntr(USF)=0,0
Exp/Cntr=0.3,0.1

Type RM Length L Ch R = 1 ,4863    ,214.1,215,211.4
XS GIS Cut Line= 2
1651214.72281375459888.141323688 1651601.4060674460071.284379792
#Sta/Elev= 30
       0  885.51     5.5  882.48    16.9  874.51      41  860.65    53.8  850.41
    74.5  836.01    81.7  829.91    98.2  812.47   103.5  808.15   107.1  806.41
   154.3   800.7   165.2  798.05   181.9  797.27   190.6  798.41   201.5  796.95
   224.9  796.07  231.82  796.96   234.2  798.15   236.1  800.23   245.1  811.93
   259.6  825.76   265.7  829.84   319.9  855.53   335.8  864.41     354  869.29
   357.6  870.91   372.1  880.49     383  886.65   419.3  904.59   427.9  909.52
#Mann= 5 ,-1,0
       0      .1       0     160     .06       0   201.5    .045       0
  231.82     .06       0     250      .1       0
Bank Sta=201.5,231.82
XS Rating Curve= 0 ,0
Exp/Cntr(USF)=0,0
Exp/Cntr=0.3,0.1

Type RM Length L Ch R = 1 ,4648    ,208.2,206.3,202.6
XS GIS Cut Line= 3
1651088.17891049460064.4309848391651368.30893208460185.029333117
1651515.49589258 460183.13014653
#Sta/Elev= 30
       0  919.83     7.5  913.33      11   911.2    21.7  907.99    32.5  902.95
    46.7  894.07    61.7  878.76    71.7  867.19      88  854.73    93.2  851.96
   104.6  848.58   129.1  832.66   139.6  828.24   162.7  812.65   181.5  798.73
  188.76794.9693   196.8  793.84   211.5   793.7  224.26794.9698   241.4  797.95
   282.5  798.36   296.8  800.28   301.4  802.05   333.5   818.9   343.4  825.31
   353.2  830.48   399.2  847.99   425.4  860.26   441.8  865.77   452.2   870.6
#Mann= 3 ,-1,0
       0      .1       0  188.76    .045       0  224.26      .1       0
Bank Sta=188.76,224.26
XS Rating Curve= 0 ,0
Exp/Cntr(USF)=0,0
Exp/Cntr=0.3,0.1

Type RM Length L Ch R = 1 ,4442    ,254.4,252.1,250.2
XS GIS Cut Line= 6
1651009.45216056460286.2380595691651094.01334314460308.725547407
1651166.49416931460328.0004432391651263.13505214460353.700523067
1651335.61587831460372.975418914 1651420.1770609460395.462578658
#Sta/Elev= 30
       0  918.36    20.6   908.6    34.2  903.65    47.8  895.91      58  891.74
      75  878.93   115.7  856.47   128.9  844.19   146.3  831.54   156.4  820.55
   163.2  814.21     170  805.04   177.2  800.83   183.6  795.25   188.3792.5953
   193.8  791.77   217.5  791.44   230.8  792.58   241.3  795.27   261.7  796.72
   275.3  795.95   289.8  797.17   354.2  798.63   359.6  800.84   366.9  805.64
   383.9   819.9   390.7  824.75   399.8  829.79   416.6  837.47     425  842.58
#Mann= 3 ,-1,0
       0      .1       0   188.3    .045       0   230.8      .1       0
#XS Ineff= 2 , 0
                          299.89          810.74
Permanent Ineff=
       F       F
Bank Sta=188.3,230.8
XS Rating Curve= 0 ,0
Exp/Cntr(USF)=0,0
Exp/Cntr=0.3,0.1

Type RM Length L Ch R = 1 ,4190    ,280,289.8,298.7
XS GIS Cut Line= 2
1650961.30654109 460555.897099421651382.97093196460621.761815209
#Sta/Elev= 30
       0   878.5    25.8  869.25      39  863.07    52.3  857.79      81  849.83
    92.2  844.09   112.1  835.33   128.7  828.18     142  823.49   151.9  818.76
   158.6  814.51   165.2  807.69   172.9  796.59   175.2  794.09   178.5  791.59
  188.65789.9064   195.1     789   208.4  788.72   221.7  788.95  226.52 789.907
     235  792.77   248.2  795.21   264.8  795.83   304.7  795.24   331.3   796.7
   344.5  798.18   357.8  803.19   364.5  805.04   394.3  816.44   426.8  832.25
#Mann= 3 ,-1,0
       0      .1       0  188.65    .045       0  226.52      .1       0
Bank Sta=188.65,226.52
XS Rating Curve= 0 ,0
Exp/Cntr(USF)=0,0
Exp/Cntr=0.3,0.1