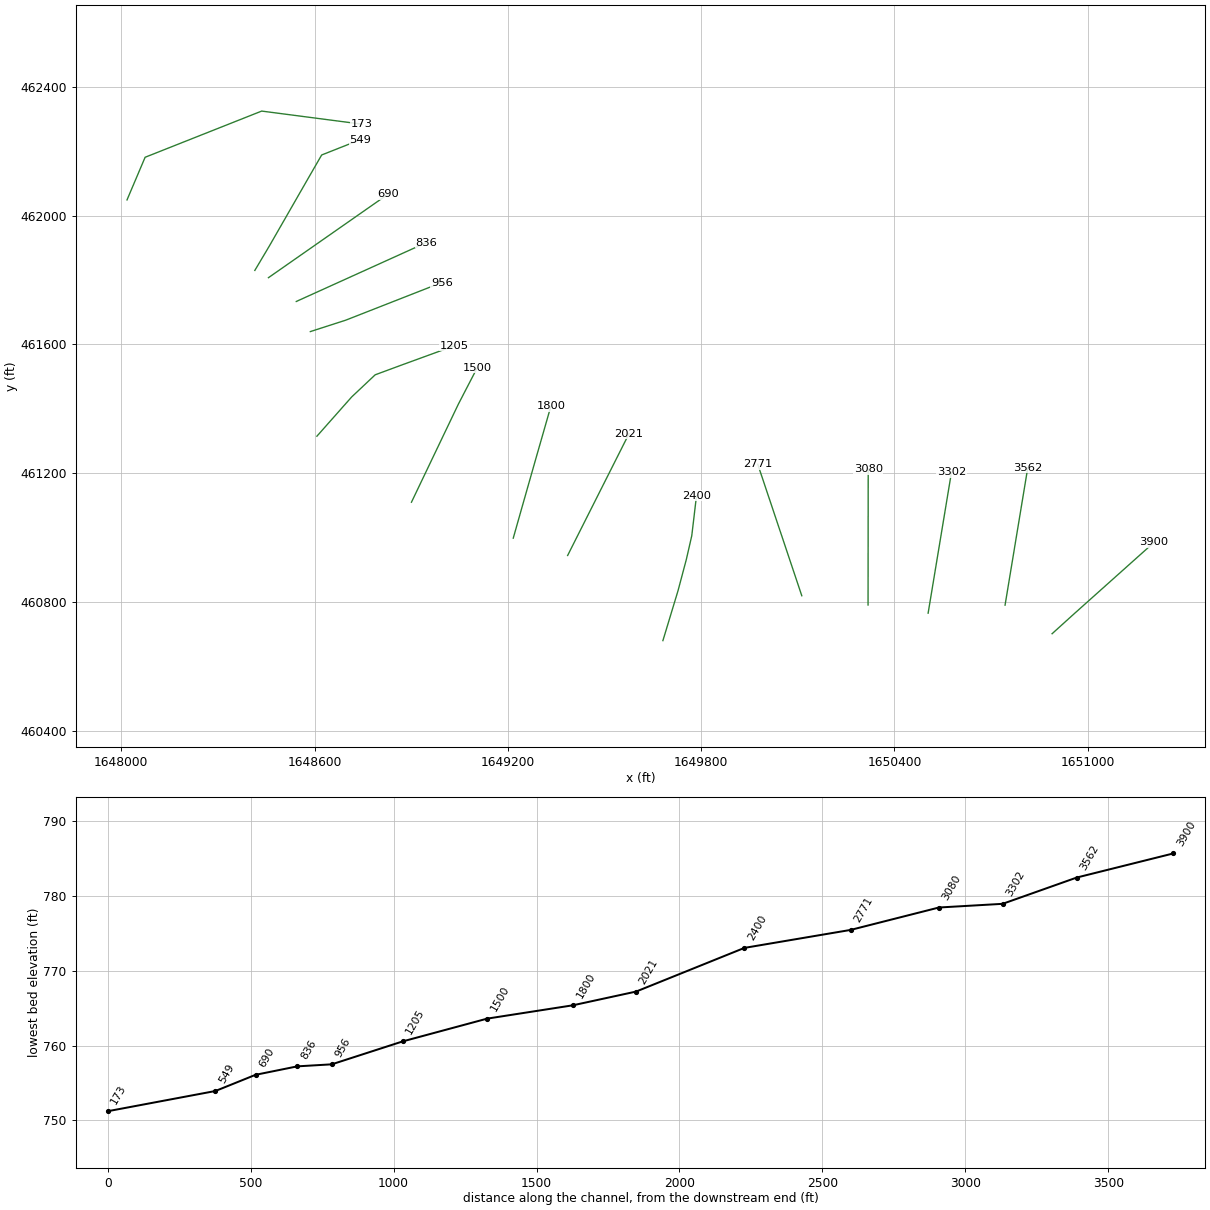
HEC-RAS study LaurelRnI.prj: LaurelRnI

--- LaurelRnI.g01 (geometry) --- (continued)

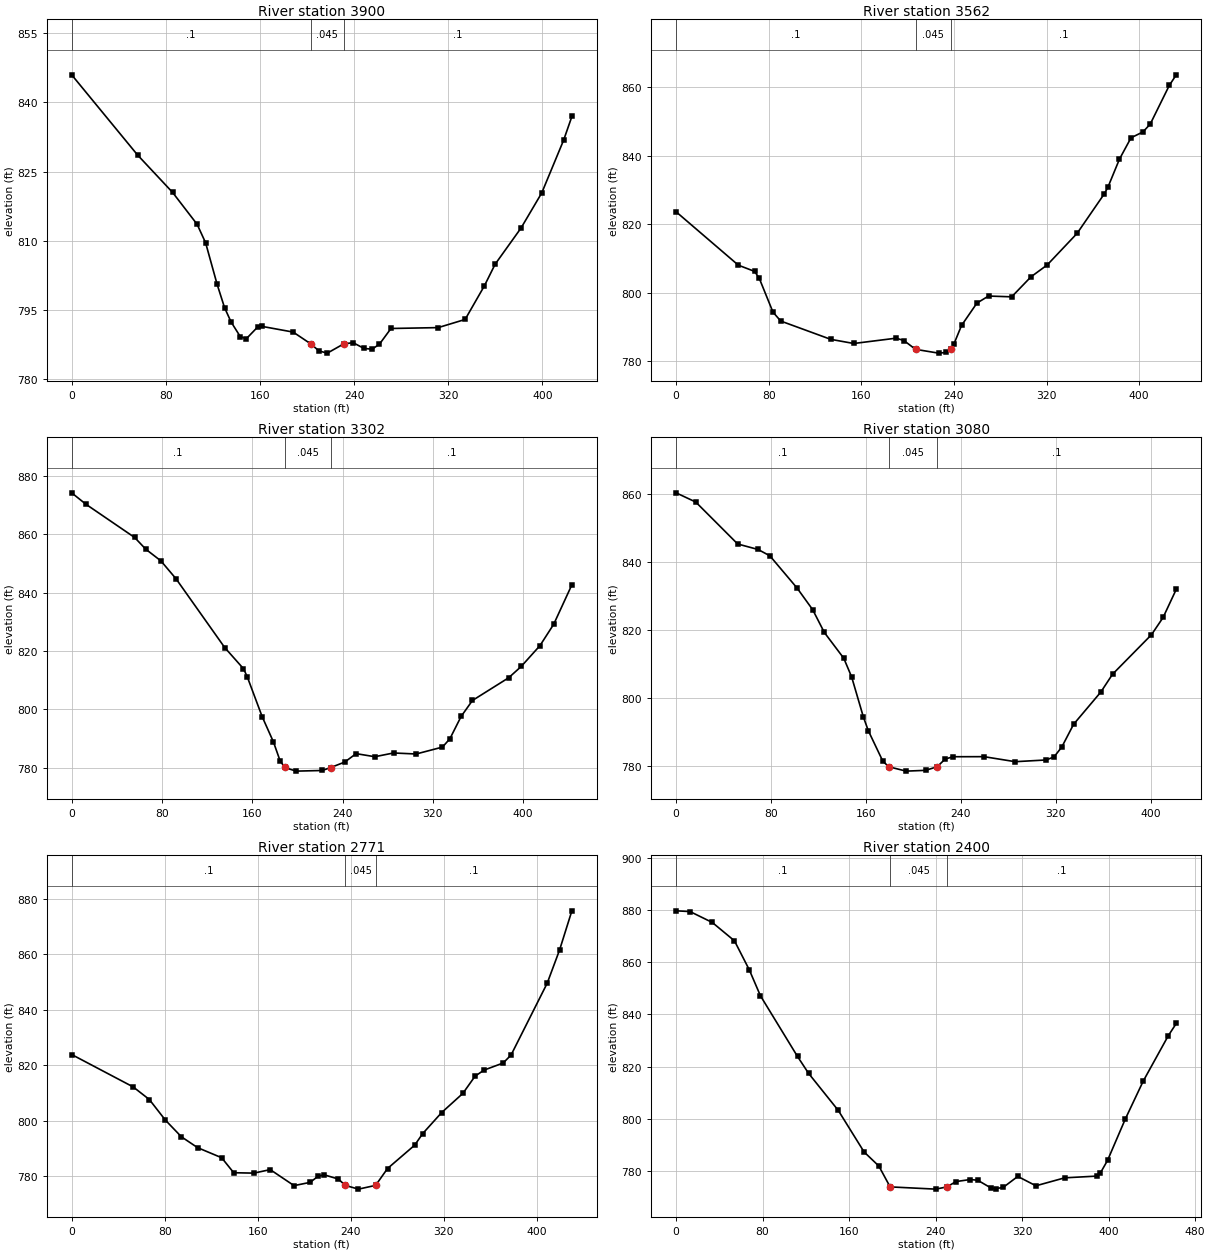
Type RM Length L Ch R = 1 ,3900    ,329.8,338.1,349.1
XS GIS Cut Line= 6
1650889.43201293460702.1372925041650954.30589892460760.856007084
1651010.23032776460810.8306446671651084.79513925460877.464697748
1651140.71989617460927.4393353461651205.96386017 460985.74400875
#Sta/Elev= 30
       0  845.95      56  828.57    85.7  820.48   106.6  813.55   113.8  809.55
   123.6  800.53   129.9  795.49   135.4  792.41   143.3   789.2   148.4  788.76
   158.1  791.32   161.8  791.43   188.2   790.2  203.16787.6411   210.2  786.11
   217.2  785.64   231.1787.6385   239.1  787.91   248.4  786.65   255.3   786.5
   261.5  787.58   271.3  790.98   311.4  791.17   334.3  792.94   350.6  800.19
   359.8  804.91   381.8  812.75   399.4  820.36     418   831.8     425  836.92
#Mann= 3 ,-1,0
       0      .1       0  203.16    .045       0   231.1      .1       0
Bank Sta=203.16,231.1
XS Rating Curve= 0 ,0
Exp/Cntr(USF)=0,0
Exp/Cntr=0.3,0.1

Type RM Length L Ch R = 1 ,3562    ,260.6,259.4,256.7
XS GIS Cut Line= 2
1650743.46522037460790.9194751351650813.91805634461217.226157337
#Sta/Elev= 30
       0  823.65    53.8  808.07    67.8  806.26    71.8  804.29    83.7  794.38
    90.4  791.78   133.6  786.44   153.5  785.23   190.1  786.78   196.8  786.09
  206.85783.5275   226.7  782.42   233.3  782.61  237.28783.5269     240  785.07
   246.6  790.49   259.9  797.02   269.9  799.07   289.9  798.84   306.5  804.65
   320.6  808.14   346.4  817.34   369.7  828.77     373  830.78     383  838.99
     393  845.23   403.3  846.93   409.6  849.22   426.1  860.52   432.1  863.59
#Mann= 3 ,-1,0
       0      .1       0  206.85    .045       0  237.28      .1       0
Bank Sta=206.85,237.28
XS Rating Curve= 0 ,0
Exp/Cntr(USF)=0,0
Exp/Cntr=0.3,0.1

Type RM Length L Ch R = 1 ,3302    ,219,222.6,225.9
XS GIS Cut Line= 2
1650504.65812873460765.9938482121650577.10171302461203.198306878
#Sta/Elev= 30
       0  874.11    12.5  870.24    55.8  858.83    65.7  854.81      79  850.85
    92.4  844.74   135.6  821.18   152.2  813.96   155.5  811.26   168.8  797.52
   178.8  788.87   184.6   782.5188.8298780.1536   198.8  778.91     222  779.13
  229.59  780.15     242  782.02     252  784.89   268.6  783.84   285.2  785.12
   305.2  784.77   328.5  787.13   335.1  789.97   345.1  797.64   355.1  803.08
   387.2  810.85   398.3  814.71   414.9  821.83   427.1  829.15   443.2  842.65
#Mann= 3 ,-1,0
       0      .1       0188.8298    .045       0  229.59      .1       0
Bank Sta=188.8298,229.59
XS Rating Curve= 0 ,0
Exp/Cntr(USF)=0,0
Exp/Cntr=0.3,0.1

Type RM Length L Ch R = 1 ,3080    ,305.3,308.8,308.4
XS GIS Cut Line= 2
1650318.19573907460791.2543222881650318.65001801 461212.64808251
#Sta/Elev= 30
       0  860.39    16.6  857.67    51.9  845.32    69.1   843.7      79  841.84
   101.9  832.36   115.1  825.96   124.9  819.26   141.3  811.65   147.9  806.17
   157.7  794.47   161.9  790.36   174.1   781.4  179.12  779.71   193.8  778.42
   210.2  778.65     220  779.72   226.6  781.95   233.2  782.66   259.4  782.68
   285.7   781.2   311.9  781.71   318.5  782.64     325  785.55   334.9  792.22
   357.8   801.7   367.7  806.96   400.5   818.6   410.3  823.68   421.4  831.98
#Mann= 3 ,-1,0
       0      .1       0  179.12    .045       0     220      .1       0
Bank Sta=179.12,220
XS Rating Curve= 0 ,0
Exp/Cntr(USF)=0,0
Exp/Cntr=0.3,0.1

Type RM Length L Ch R = 1 ,2771    ,378.7,371.6,340.5
XS GIS Cut Line= 2
1650112.51460351460820.0491301721649975.85874761461228.105551729
#Sta/Elev= 30
       0  823.87    52.9  812.21    66.8  807.68    80.6  800.27    94.4  794.26
   108.3  790.36     129  786.73   139.4  781.33   156.7  781.19   170.8  782.45
   191.3  776.69   205.2  777.87   212.1  780.13   217.3  780.57   229.4  779.06
   235.4  776.77   246.7  775.43  261.46  776.78   271.7  782.84   295.1  791.26
     302  795.43   318.3  802.99   336.5  809.87     347  816.06   354.6  818.24
   371.2  820.82     378   823.7   409.1  849.56   419.7  861.47   430.3  875.58
#Mann= 3 ,-1,0
       0      .1       0   235.4    .045       0  261.46      .1       0
Bank Sta=235.4,261.46
XS Rating Curve= 0 ,0
Exp/Cntr(USF)=0,0
Exp/Cntr=0.3,0.1

Type RM Length L Ch R = 1 ,2400    ,381,378.9,357
XS GIS Cut Line= 6
1649681.40030825 460680.725918011649706.74408959 460764.43933326
1649728.47206451460836.2059220081649754.19773485460932.970492259
1649771.01200567461006.4572219251649785.67798685461130.254218429
#Sta/Elev= 30
       0  879.67    12.9  879.39    33.5  875.21      54  868.17    67.7  857.07
      78  847.13   112.3  823.86   122.6  817.36     150  803.19   173.9  787.26
   187.5  781.89  197.95773.8875     240  773.03  250.49773.8724   258.8  775.92
   272.1  776.71     279  776.43   291.5   773.4   295.8  773.24   302.5  773.68
     316   777.9   332.8  774.31   359.4  777.36   389.1  778.02   392.4  779.22
     399  784.01   415.5  799.93     432   814.4   455.2  831.81   462.6  836.52
#Mann= 3 ,-1,0
       0      .1       0  197.95    .045       0  250.49      .1       0
Bank Sta=197.95,250.49
XS Rating Curve= 0 ,0
Exp/Cntr(USF)=0,0
Exp/Cntr=0.3,0.1

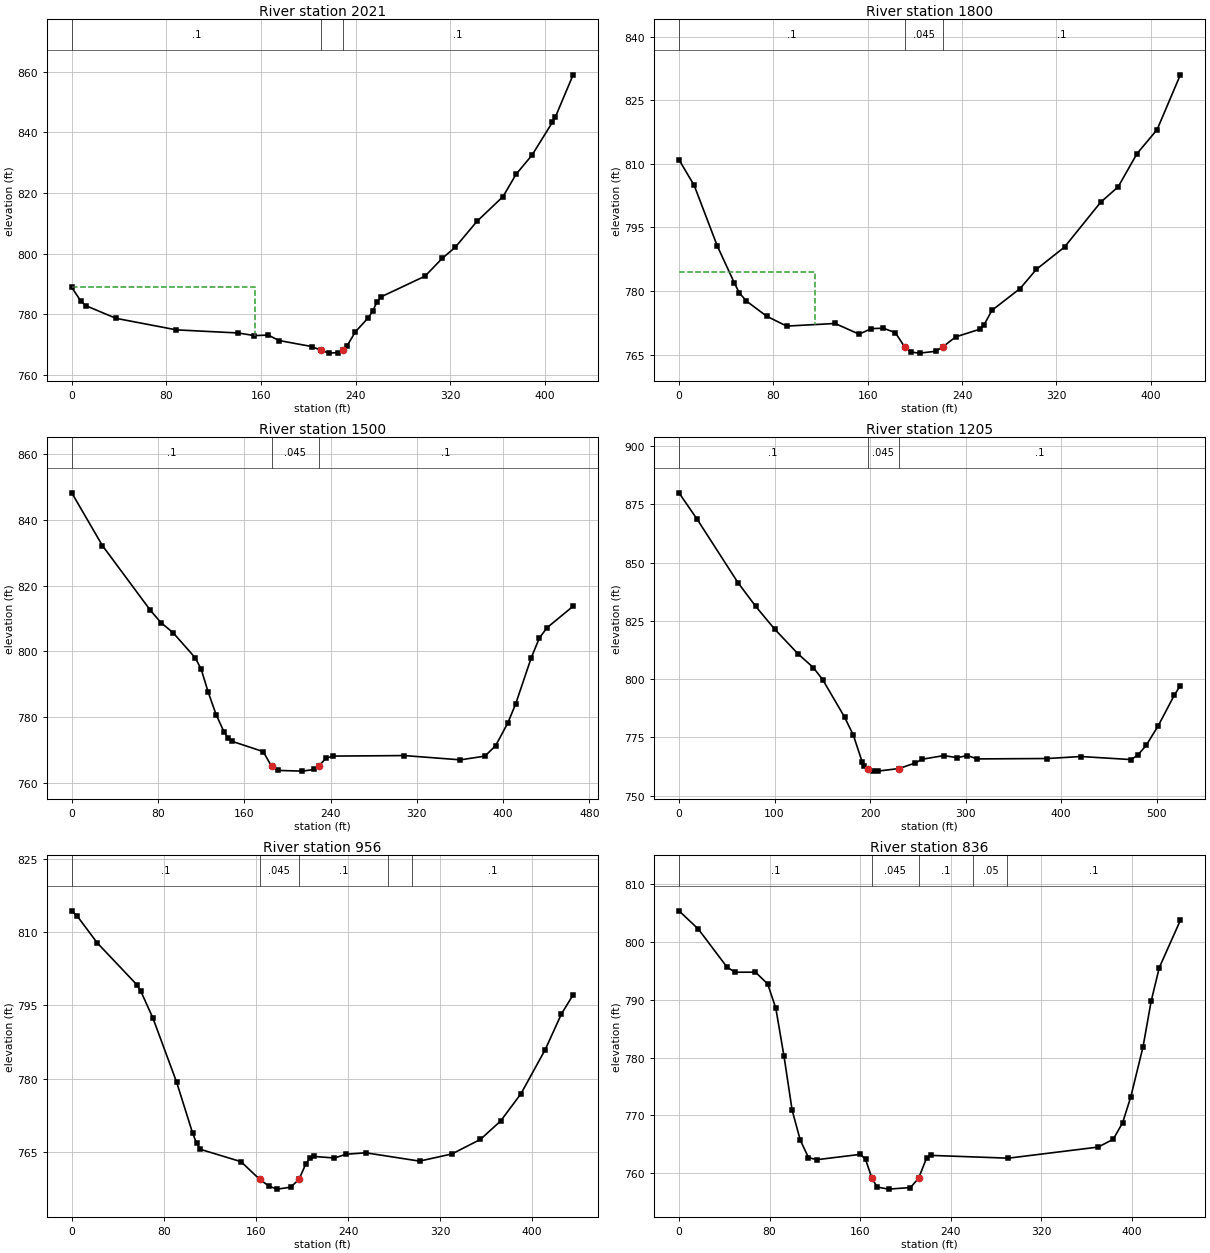
Type RM Length L Ch R = 1 ,2021    ,218.2,220.8,221.3
XS GIS Cut Line= 2
1649385.67616217460945.071846008 1649576.3424365461323.363383003
#Sta/Elev= 30
       0  788.86     7.8   784.3    11.7  782.88    37.4  778.67    88.4  774.87
   140.3  773.85   154.4  772.98     166  773.15   175.1  771.36   202.8  769.37
   210.6  768.13   217.4   767.2   224.8  767.38   229.4  768.13   232.6  769.57
   239.5  774.15   250.5  778.85   254.2  780.99   257.9  784.13   261.5  785.78
   298.5  792.58     313  798.43     324  802.09   342.4  810.66   364.4  818.81
   375.4  826.16   388.9  832.48     406  843.24   408.5  844.94   423.6  858.95
#Mann= 3 ,-1,0
       0      .1       0   210.6    .045       0   229.4      .1       0
#XS Ineff= 2 , 0
          155.17  788.93
Permanent Ineff=
       F       F
Bank Sta=210.6,229.4
XS Rating Curve= 0 ,0
Exp/Cntr(USF)=0,0
Exp/Cntr=0.3,0.1

Type RM Length L Ch R = 1 ,1800    ,304.1,299.9,297.4
XS GIS Cut Line= 6
1649216.89139476  460998.87291951649240.74764626461083.077147424
1649261.26204093 461155.231858761649288.68619867461251.398005009
1649309.35118359461323.4870996771649333.46005926461407.588309422
#Sta/Elev= 30
       0  810.96    12.9  804.91    32.5  790.61      47  781.89    51.1  779.58
    57.2  777.64    74.3  774.08    91.3  771.74   132.3  772.36   152.7  769.84
     163  771.14   173.2  771.25   183.4  770.19   191.2766.8812   197.1   765.6
   203.9  765.37   217.6   765.8  223.81766.8837   234.6   769.2   255.1  771.01
   258.5  771.98   265.3  775.46   289.2   780.6   302.9   785.1   326.8  790.37
   357.5  800.95   372.3  804.57   388.2  812.37   405.3  818.06     425  830.97
#Mann= 3 ,-1,0
       0      .1       0   191.2    .045       0  223.81      .1       0
#XS Ineff= 2 , 0
           115.6  784.57
Permanent Ineff=
       F       F
Bank Sta=191.2,223.81
XS Rating Curve= 0 ,0
Exp/Cntr(USF)=0,0
Exp/Cntr=0.3,0.1

Type RM Length L Ch R = 1 ,1500    ,303.4,295.5,289.1
XS GIS Cut Line= 6
1648900.89858842461110.3451375071648938.65113759461189.281659424
1648971.01032484461256.9416290821649014.15590784461347.155031338
1649046.51509508461414.815001011 1649105.1590248461527.937209574
#Sta/Elev= 30
       0  848.19    28.4  832.17    72.8  812.53    82.6  808.77    93.9   805.7
   114.6  798.01     120  794.59   126.6  787.54   133.9  780.76   141.1  775.59
   144.8  773.79   148.4  772.68   177.5  769.53  185.39765.0091   190.9  763.81
   213.9  763.59   224.8  764.09  228.88765.0067   235.7  767.54   242.5  768.16
   308.4  768.32   360.4  767.02   383.1  768.15     393   771.3   404.2  778.13
   411.6  783.98   426.1  798.07   433.6  804.04   440.7  807.18   464.9  813.71
#Mann= 3 ,-1,0
       0      .1       0  185.39    .045       0  228.88      .1       0
Bank Sta=185.39,228.88
XS Rating Curve= 0 ,0
Exp/Cntr(USF)=0,0
Exp/Cntr=0.3,0.1

Type RM Length L Ch R = 1 ,1205    ,251,248.1,238.6
XS GIS Cut Line= 6
1648607.48250858 461315.324058251648665.49814059461380.825239584
1648715.22605951461436.9691561761648788.27971917461505.849595845
1648870.85042018461536.3626581731649034.08840164461595.856892043
#Sta/Elev= 30
       0  879.96      19  868.62    61.7  841.43    80.3  831.25     100  821.53
   124.7  810.83   140.7  804.94   150.5  799.73   173.3  783.73   182.5  775.96
   191.8  764.41   194.1  762.87  197.32 761.663   203.4  760.68     208  760.55
  230.31761.6632   247.5  764.07   254.5  765.66   277.3  767.21   291.3  766.31
   301.7  767.25   312.2  765.79   385.6  765.96   420.5  766.82   472.9  765.51
   479.9   767.3   488.9  771.58   501.7  780.12   518.3  793.08   524.7  797.26
#Mann= 3 ,-1,0
       0      .1       0  197.32    .045       0  230.31      .1       0
Bank Sta=197.32,230.31
XS Rating Curve= 0 ,0
Exp/Cntr(USF)=0,0
Exp/Cntr=0.3,0.1

Type RM Length L Ch R = 1 ,956     ,119.1,120.4,121.4
XS GIS Cut Line= 3
1648587.03168728461640.0064576861648696.62260574461675.320677334
1648994.90727168461792.262478551
#Sta/Elev= 30
       0  814.32       5  813.17    22.2  807.76    56.7  799.19    60.1  797.85
    70.5  792.43    91.2  779.27   104.9     769   108.4  766.89   111.8  765.61
     147   763.1   163.3759.4774   171.7  758.04   178.7  757.49   190.2  757.89
   197.4759.4874   203.4  762.67   206.9  763.86   210.4  764.16   228.2  763.85
   238.3  764.61   255.4  764.91   302.1  763.21   330.2  764.67   354.9  767.63
   372.5  771.39   390.2  776.97   411.3  785.99   425.4  793.28   435.5  797.16
#Mann= 5 ,-1,0
       0      .1       0   163.3    .045       0   197.4      .1       0
  275.14     .05       0  295.14      .1       0
Bank Sta=163.3,197.4
XS Rating Curve= 0 ,0
Exp/Cntr(USF)=0,0
Exp/Cntr=0.3,0.1

Type RM Length L Ch R = 1 ,836     ,141.8,146.2,149.3
XS GIS Cut Line= 2
1648543.42877573461733.4802461731648946.62917741 461916.08468341
#Sta/Elev= 30
       0   805.4    17.1  802.24    42.3  795.68    49.5  794.77    67.5  794.78
    78.3  792.74    85.5  788.53    92.7  780.25    99.9  770.88   107.1  765.69
   114.3  762.69   121.5  762.31   160.2  763.24   164.7  762.37  170.35  759.09
     175  757.58     185  757.22   204.3  757.49   211.5  759.09   218.7  762.66
   222.3  763.06   290.8  762.58     370   764.5   383.3  765.84   391.6   768.7
   398.8  773.16   409.6  781.79   416.8  789.73     424  795.57   442.6  803.75
#Mann= 5 ,-1,0
       0      .1       0  170.35    .045       0   211.5      .1       0
     260     .05       0     290      .1       0
Bank Sta=170.35,211.5
XS Rating Curve= 0 ,0
Exp/Cntr(USF)=0,0
Exp/Cntr=0.3,0.1

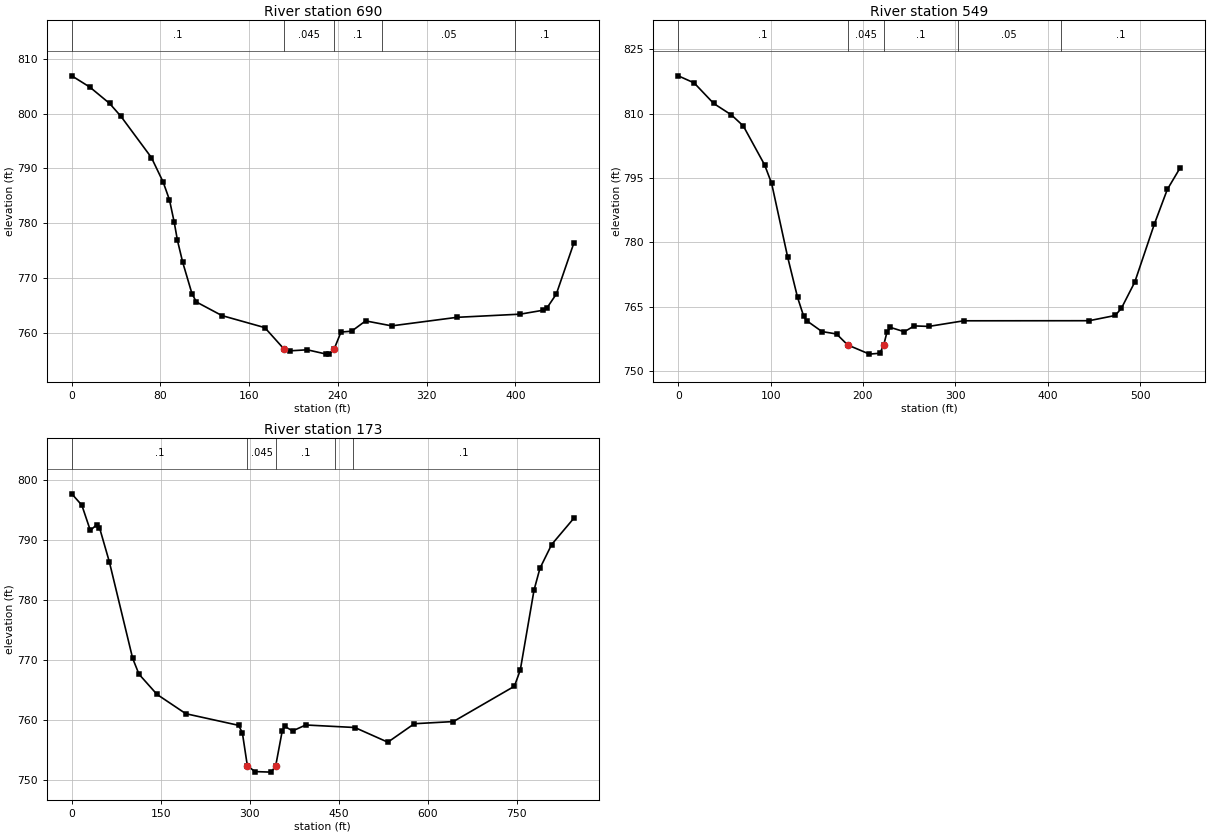
Type RM Length L Ch R = 1 ,690     ,129.7,140.3,149.3
XS GIS Cut Line= 2
1648456.99446926461807.3155906981648828.28544703 462066.55455983
#Sta/Elev= 30
       0  806.91    16.3  804.85    34.1  801.87    44.3  799.52    71.8  791.99
    82.4  787.52    88.1  784.27    92.4  780.17    95.3  776.86     100  772.89
   108.4  767.13   112.4  765.61   135.4  763.13   174.1  760.93   191.2  757.07
   196.6  756.69   212.4  756.88   229.6  756.09   232.4  756.13   236.7  757.06
   242.8  760.12   252.4  760.28     265  762.16   288.5  761.25   347.4  762.81
   404.5  763.39   425.2  764.11   428.5  764.51     437  767.06   452.8  776.37
#Mann= 5 ,-1,0
       0      .1       0   191.2    .045       0   236.7      .1       0
     280     .05       0     400      .1       0
Bank Sta=191.2,236.7
XS Rating Curve= 0 ,0
Exp/Cntr(USF)=0,0
Exp/Cntr=0.3,0.1

Type RM Length L Ch R = 1 ,549     ,391.2,376.9,361.9
XS GIS Cut Line= 6
1648414.72467211461829.8376651951648459.61204952461905.338498438
1648496.95219794461970.3823316051648584.07899219462122.151713113
1648622.19575727  462188.16816961648742.63084759462235.861500644
#Sta/Elev= 30
       0  818.81    17.2  817.16    38.3  812.38    57.6  809.69    70.4  807.14
    93.5  798.06   101.1  793.75   118.5  776.53   129.2  767.14   135.8  762.77
   138.9  761.75   155.6  759.19   171.4  758.63   183.4  756.08     207  753.93
   218.3  754.14  222.44 756.016   225.9  758.98   229.7  760.16   244.8  759.15
   255.5  760.51   271.3  760.39   309.1   761.7   444.9  761.72   473.1  762.94
   479.8  764.61   494.3  770.73   515.4  784.19   529.5  792.31   543.6  797.43
#Mann= 5 ,-1,0
       0      .1       0   183.4    .045       0  222.44      .1       0
  302.84     .05       0  414.07      .1       0
Bank Sta=183.4,222.44
XS Rating Curve= 0 ,0
Exp/Cntr(USF)=0,0
Exp/Cntr=0.3,0.1

Type RM Length L Ch R = 1 ,173     ,,,
XS GIS Cut Line= 4
1648018.00414213462048.7680364861648074.16979684462181.074436109
1648435.96484167462324.463023431 1648746.8953061462283.890889566
#Sta/Elev= 30
       0  797.63      17  795.73    31.3  791.52      42  792.49    46.7  792.01
    63.4  786.27   102.6  770.22   113.3  767.56   143.7  764.19   192.3  760.97
   281.3  759.03   287.6   757.8  295.96752.3327   308.6  751.32   336.4  751.23
  343.93752.3317   354.7  758.03   359.1  758.86   372.3   758.1   394.5  759.09
   477.2  758.67   532.9  756.22   577.5   759.3   643.4  759.66   746.3  765.55
   756.2  768.26   779.4  781.59   789.3   785.2   809.1  789.18   846.5  793.56
#Mann= 5 ,-1,0
       0      .1       0  295.96    .045       0  343.93      .1       0
  443.73     .05       0  473.73      .1       0
Bank Sta=295.96,343.93
XS Rating Curve= 0 ,0
Exp/Cntr(USF)=0,0
Exp/Cntr=0.3,0.1
LCMann Table=0

Chan Stop Cuts=-1
Use User Specified Reach Order=0
Composite Channel Slope=5